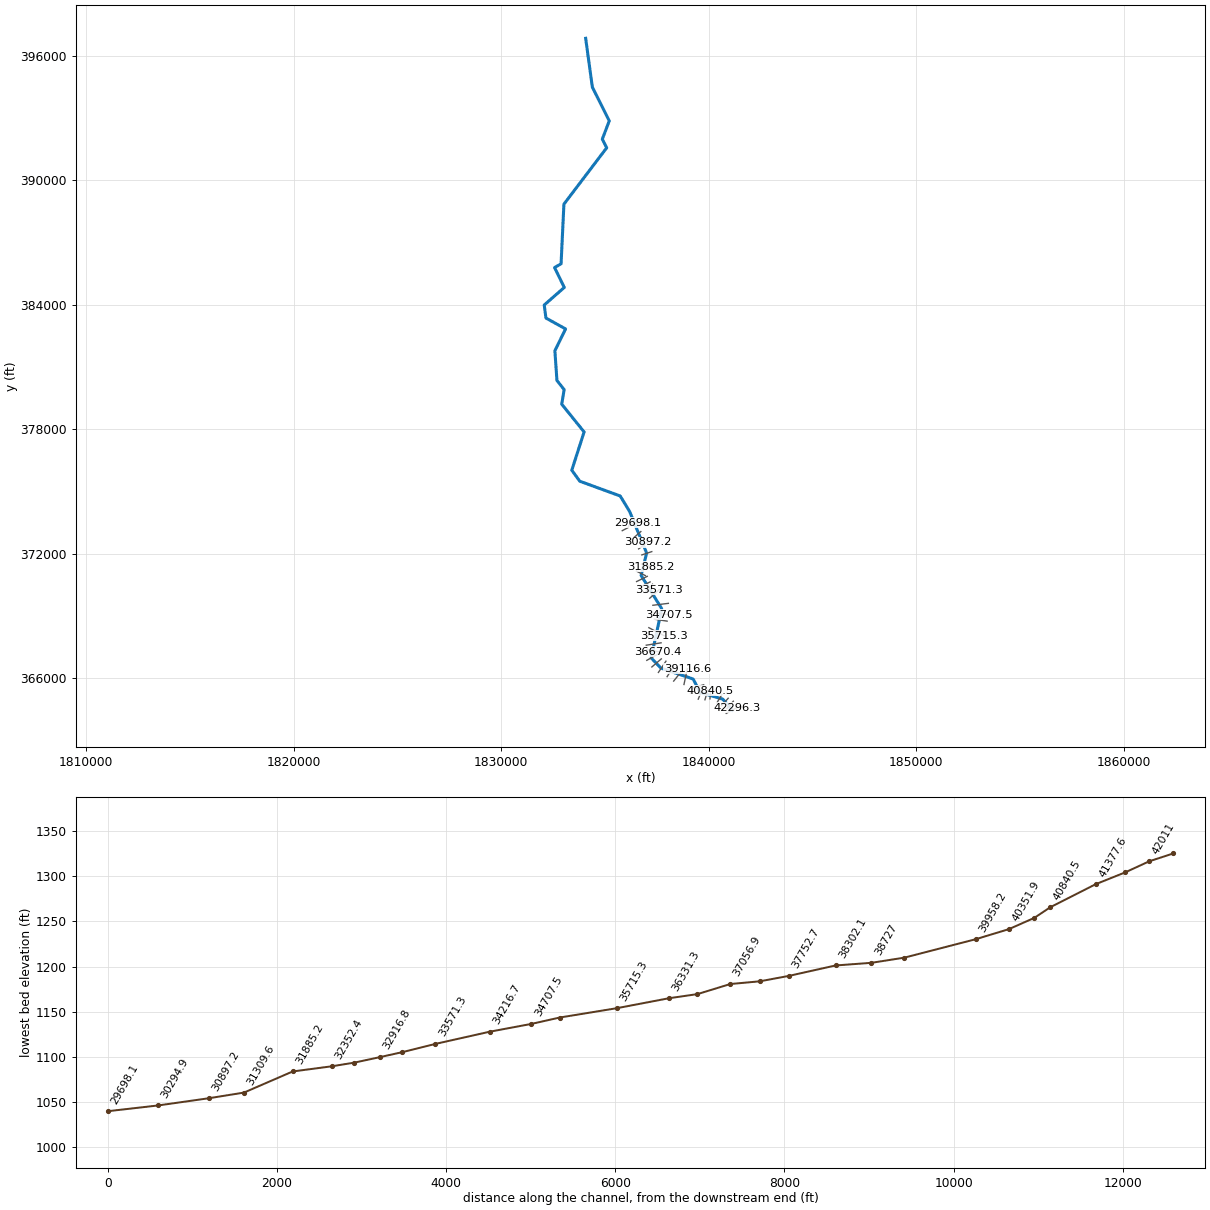
--- BoothsCk.prj (project) ---

Proj Title=BoothsCk
Current Plan=p01
Default Exp/Contr=0,0
English Units
Geom File=g01
Flow File=f01
Plan File=p01
BEGIN DESCRIPTION:
END DESCRIPTION:
DSS Export Rating Curves= 0
DSS Export Rating Curve Sorted= 0
DSS Export Volume Flow Curves= 0
DXF Filename=m:\Didavi\Junko\BoothsCk.
DXF OffsetX= 0
DXF OffsetY= 0
DXF ScaleX= 0
DXF ScaleY= 0

--- BoothsCk.p01 (plan) ---

Plan Title=Floodplain
Program Version=4.00
Geom File=g01
Flow File=f01
K Sum by GR=0
Std Step Tol=0.01
Critical Tol=0.01
Num of Std Step Trials=20
Max Error Tol=0.3
Flow Tol Ratio=0.001
Split Flow NTrial=30
Split Flow Tol=0.02
Split Flow Ratio=0.02
Log Output Level=0
Friction Slope Method=1
Unsteady Friction Slope Method=2
Unsteady Bridges Friction Slope Method=1
Global Log Level=0
CheckData=False
Run HTab=0
Run UNet=0
Run PostProcess=0
UNET Theta=0
UNET Theta Warmup=0
UNET ZTol=0
UNET ZSATol=0
UNET MxIter=0
UNET MaxInSteps=0
UNET DtIC=0
UNET DtMin=0
UNET MaxCRTS=0
UNET WFStab=0
UNET SFStab=0
UNET WFX=0
UNET SFX=0
UNET DSS MLevel=0
UNET DZMax Abort=0
UNET Convert EG Bridges=0
UNET Use Existing IB Tables=0
UNET Froude Limit=0
UNET Froude Power=0
Write IC File=0
Echo Input=False
Echo Output=False
Write Detailed=0

--- BoothsCk.f01 (steady flow) ---

Flow Title=NFF Regression Equation
Program Version=4.10
Number of Profiles= 1
Profile Names=P100yr
River Rch & RM=BoothsCk,Main            ,42296.3
     874
River Rch & RM=BoothsCk,Main            ,39116.6
    1506
River Rch & RM=BoothsCk,Main            ,38727
    1644
River Rch & RM=BoothsCk,Main            ,36670.4
    1752
River Rch & RM=BoothsCk,Main            ,33571.3
    1798
River Rch & RM=BoothsCk,Main            ,33179.7
    1898
River Rch & RM=BoothsCk,Main            ,32352.4
    1951
River Rch & RM=BoothsCk,Main            ,27616.4
    2063
River Rch & RM=BoothsCk,Main            ,25481.5
    2431
River Rch & RM=BoothsCk,Main            ,22963.2
    3275
River Rch & RM=BoothsCk,Main            ,18283.1
    3420
River Rch & RM=BoothsCk,Main            ,8885.4
    3681
River Rch & RM=BoothsCk,Main            ,6181.7
    3722
River Rch & RM=BoothsCk,Main            ,5397.1
    4054
River Rch & RM=BoothsCk,Main            ,4503.5
    4059
Boundary for River Rch & Prof#=BoothsCk,Main            , 1
Up Type= 0
Dn Type= 3
Dn Slope=0.007218
DSS Import GetInterval= 0
DSS Import GetPeak= 0
DSS Import FillOption= 0

--- BoothsCk.g01 (geometry) ---

Geom Title=USGS 10m DEM
Program Version=4.10

River Reach=BoothsCk        ,Main
Reach XY= 30
     1841138.278      364460.052     1840674.718      364991.737
     1839586.055       365314.66     1839246.185      365962.866
     1837691.095      366489.998      1837225.85      366978.514
     1837731.903      369350.776     1836740.116       370953.25
      1837004.02         372035.      1836184.74      374036.785
     1835730.118      374785.157     1833783.558      375495.925
     1833396.978      376025.924     1833990.653      377871.042
     1832914.304       379208.21     1833028.237      379913.288
      1832681.05      380351.221     1832581.931      381784.937
     1833098.053       382835.95      1832150.48      383361.524
     1832069.456      383989.863     1833035.394      384835.211
      1832566.47      385794.668     1832880.436      385975.621
     1833017.367      388850.614     1835079.825      391566.582
     1834868.019      391983.248     1835203.957      392863.804
     1834387.984      394491.235     1834065.783       396842.18

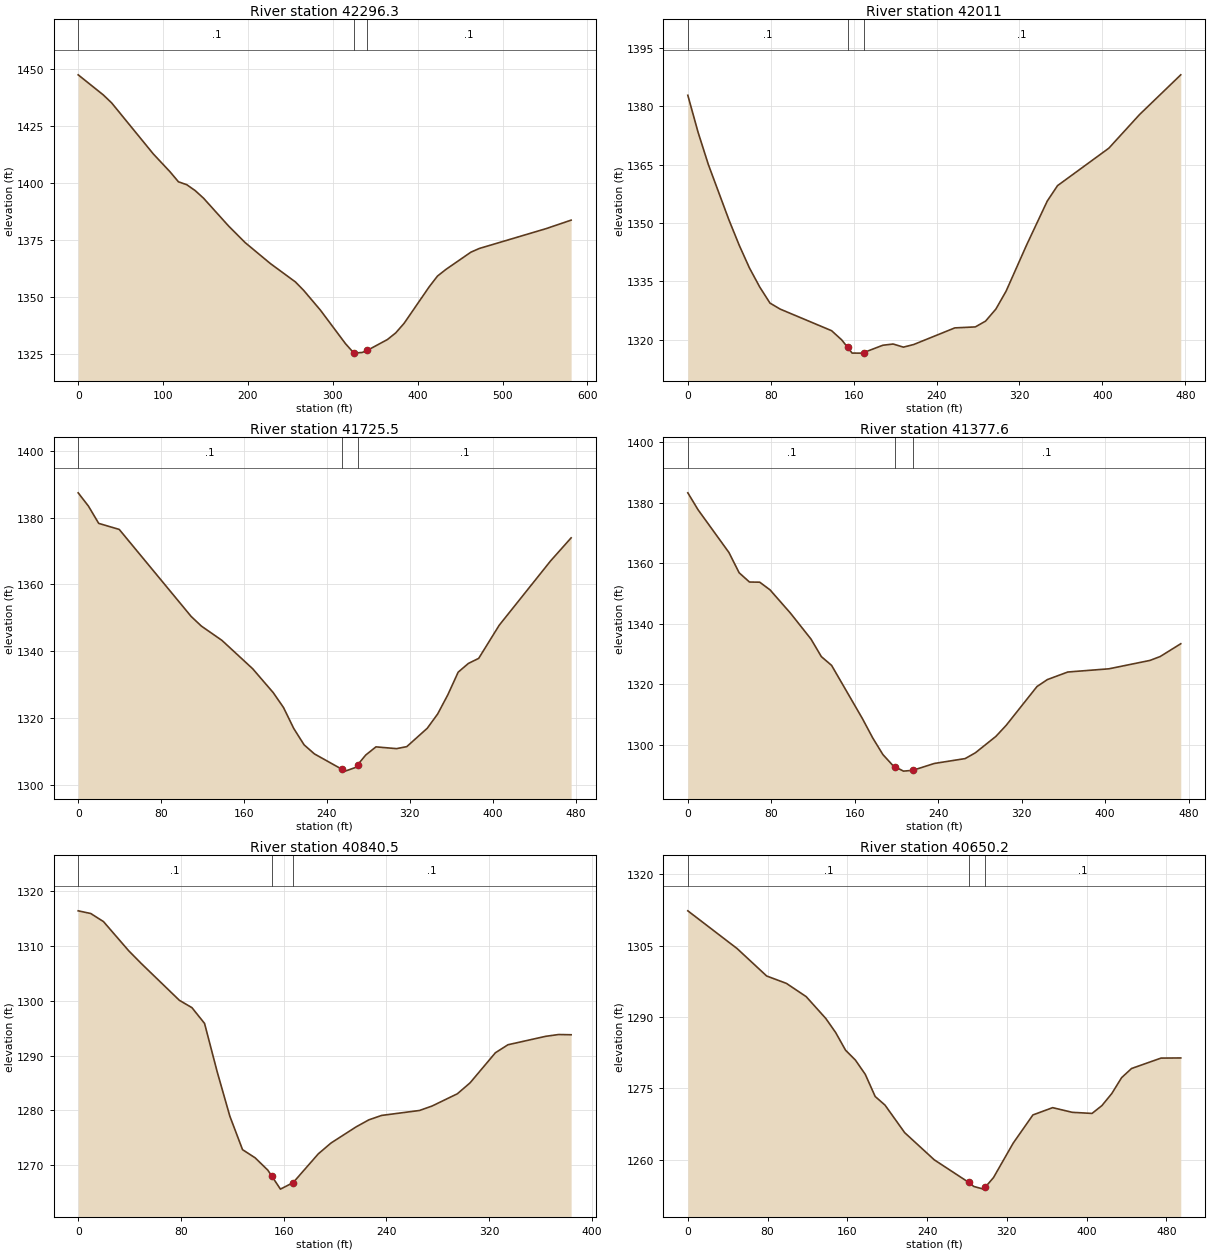
Type RM Length L Ch R = 1 ,42296.3 ,277.8,285.2,292.2
XS GIS Cut Line= 2
     1840841.408      364307.177     1841352.057      364583.977
#Sta/Elev= 30
       0  1447.4    29.5 1438.61    39.4 1435.09    88.6 1412.64   108.3 1404.81
   118.1 1400.46     128 1399.16   137.8  1396.6   147.7 1393.25   177.2 1381.05
   196.9  1373.7   226.4 1364.58     256 1356.48   265.8 1352.74   285.5 1344.07
     315 1329.37   324.9 1325.25   325.4 1325.27   334.7 1325.55   340.51326.425
   364.3  1331.2   374.1 1334.12     384 1338.33   413.5 1354.32   423.3 1359.06
   433.2 1361.97   462.7 1369.56   472.6 1371.18   551.3 1379.89   580.8 1383.62
#Mann= 3 , 0 , 0
       0      .1       0   325.4    .045       0   340.5      .1       0
Bank Sta=325.4,340.5
XS Rating Curve= 0 ,0
Exp/Cntr=0.3,0.1

Type RM Length L Ch R = 1 ,42011   ,285.7,285.5,285.4
XS GIS Cut Line= 2
     1840869.111      364534.193     1841181.688      364892.579
#Sta/Elev= 30
       0 1382.86     9.9 1373.34    19.8 1365.05    39.6 1350.86    49.5 1344.35
    59.4 1338.49    69.4 1333.54    79.3 1329.41    89.2 1327.86   138.7 1322.32
   148.6 1319.92   154.11318.052   158.5 1316.56   168.4 1316.55   169.61316.682
   188.2 1318.58   198.1 1318.89     208 1318.09     218 1318.77   257.6 1323.04
   277.4 1323.29   287.3 1324.79   297.2 1327.87   307.1  1332.5   326.9 1344.38
   346.8 1355.66   356.7 1359.62   406.2 1369.25   435.9 1377.92   475.6 1388.12
#Mann= 3 , 0 , 0
       0      .1       0   154.1    .045       0   169.6      .1       0
Bank Sta=154.1,169.6
XS Rating Curve= 0 ,0
Exp/Cntr=0.3,0.1

Type RM Length L Ch R = 1 ,41725.5 ,344.7,347.9,351
XS GIS Cut Line= 2
     1840623.451       364678.29     1840936.028      365036.676
#Sta/Elev= 30
       0 1387.38     9.9 1383.41    19.8 1378.25    39.6 1376.45     109 1350.45
   118.9 1347.56   138.7  1343.3   168.4 1334.81   188.2 1327.68   198.1 1323.24
     208 1316.97     218 1312.08   227.9 1309.39   254.7 1304.75   257.6 1304.24
   267.5 1305.32   269.7 1306.15   277.4 1309.04   287.3 1311.49   307.1 1310.96
     317 1311.55   336.8 1317.05   346.8  1321.3   356.7 1327.08   366.6  1333.8
   376.5 1336.42   386.4 1337.92   406.2 1347.82   455.7 1367.01   475.6 1373.93
#Mann= 3 , 0 , 0
       0      .1       0   254.7    .045       0   269.7      .1       0
Bank Sta=254.7,269.7
XS Rating Curve= 0 ,0
Exp/Cntr=0.3,0.1

Type RM Length L Ch R = 1 ,41377.6 ,525.4,537.1,548.9
XS GIS Cut Line= 2
     1840389.404       364814.24     1840634.938       365217.98
#Sta/Elev= 30
       0 1383.32     9.8 1377.72    39.4 1363.57    49.2 1356.85    59.1 1353.79
    68.9 1353.74    78.8  1351.2    98.4 1343.48   118.1 1334.89     128 1329.09
   137.8  1326.2   167.4 1308.55   177.2  1302.2     187 1296.67   196.9 1292.93
     1991292.561   206.7 1291.19   215.61291.452   236.3 1293.73   265.8 1295.34
   275.6 1297.25   295.3 1302.69   305.2 1306.37   334.7  1319.2   344.6 1321.49
   364.2    1324   403.6 1325.06     443 1327.84   452.8 1329.13   472.5 1333.36
#Mann= 3 , 0 , 0
       0      .1       0     199    .045       0   215.6      .1       0
Bank Sta=199,215.6
XS Rating Curve= 0 ,0
Exp/Cntr=0.3,0.1

Type RM Length L Ch R = 1 ,40840.5 ,194.9,190.3,186
XS GIS Cut Line= 2
     1840057.154      365007.036      1840084.64      365389.988
#Sta/Elev= 30
       0 1316.33     9.8 1315.84    19.7 1314.37    39.4 1309.05    49.2 1306.73
    78.8 1300.05    88.6 1298.71    98.4 1295.85   108.3    1287   118.1 1278.97
     128 1272.87   137.8 1271.39   147.7 1269.14   150.91268.015   157.5 1265.69
   167.4 1266.87     187 1272.11   196.9 1274.08   216.6 1277.04   226.4  1278.3
   236.3  1279.1   265.8    1280   275.6 1280.81   295.3 1283.04   305.2 1285.03
   324.9  1290.5   334.7 1291.96   364.2  1293.5   374.1 1293.82   383.9 1293.78
#Mann= 3 , 0 , 0
       0      .1       0   150.9    .045       0   167.4      .1       0
Bank Sta=150.9,167.4
XS Rating Curve= 0 ,0
Exp/Cntr=0.3,0.1

Type RM Length L Ch R = 1 ,40650.2 ,300.8,298.4,295.3
XS GIS Cut Line= 2
     1839814.976      364963.022     1839952.187      365438.001
#Sta/Elev= 30
       0 1312.29    49.4 1304.37    79.1  1298.6    98.9 1297.05   118.7 1294.27
   138.4 1289.68   148.3 1286.72   158.2 1283.02   168.1 1280.94     178 1277.94
   187.9  1273.3   197.8 1271.48   217.5  1265.7   247.2 1259.99   281.71255.257
   286.8  1254.4   296.6 1253.84   298.1  1254.2   306.5 1256.24   326.3 1263.49
   346.1 1269.42   365.9 1270.95   385.6 1269.97   405.4 1269.74   415.3 1271.38
   425.2 1273.91   435.1 1277.26     445 1279.17   474.6 1281.36   494.4 1281.39
#Mann= 3 , 0 , 0
       0      .1       0   281.7    .045       0   298.1      .1       0
Bank Sta=281.7,298.1
XS Rating Curve= 0 ,0
Exp/Cntr=0.3,0.1

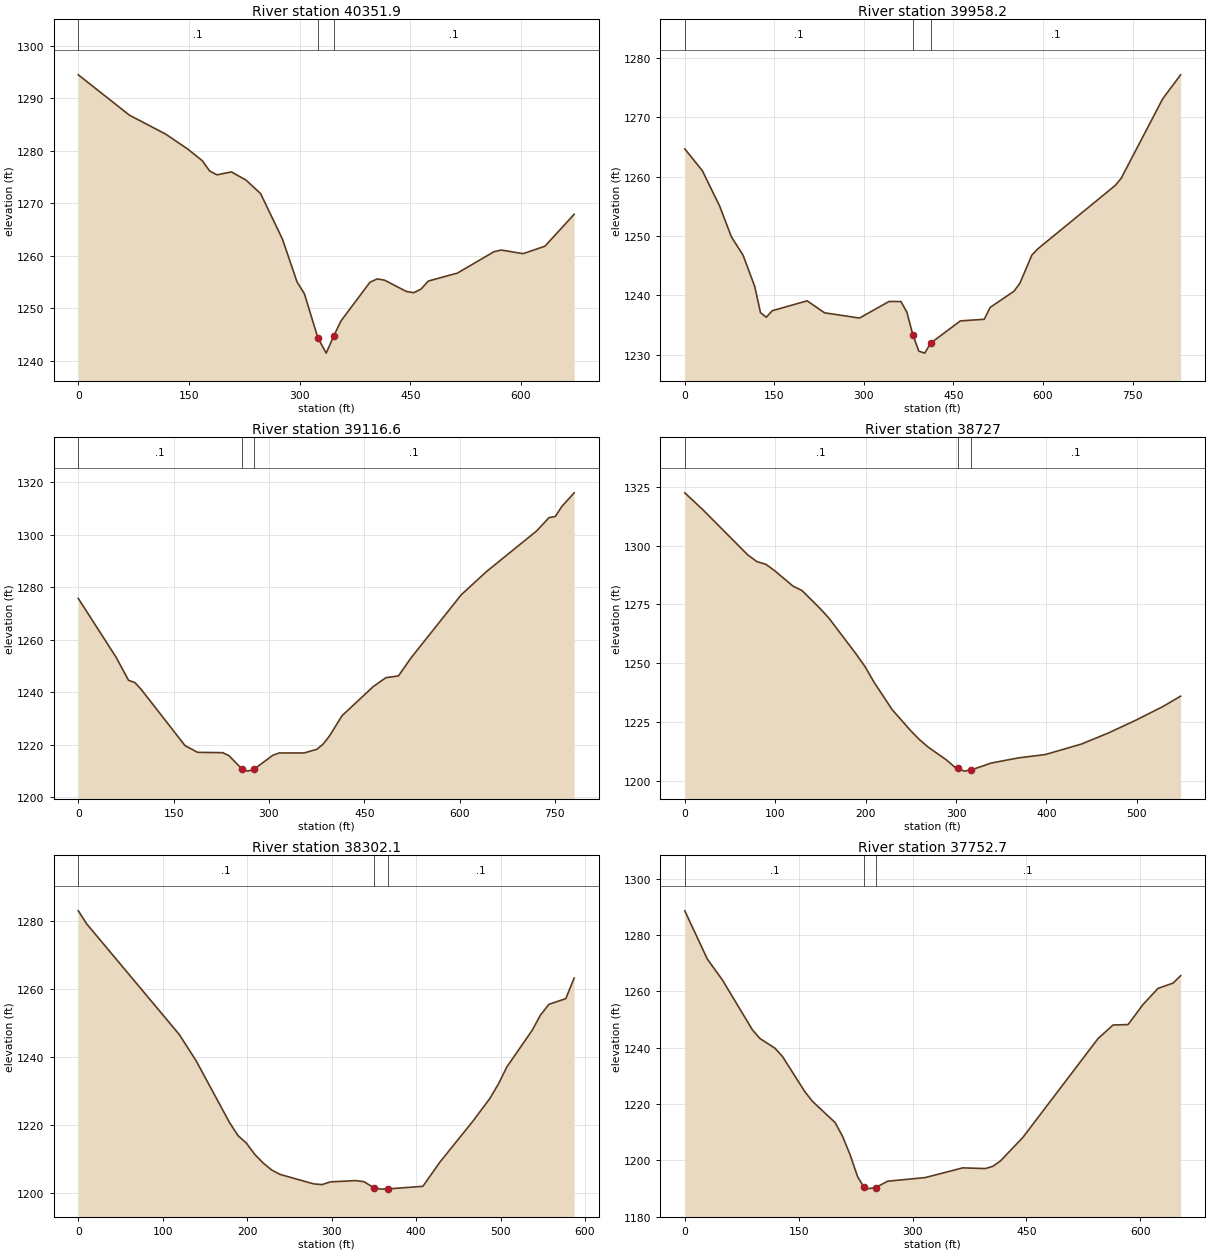
Type RM Length L Ch R = 1 ,40351.9 ,415.3,393.7,372.9
XS GIS Cut Line= 2
      1839492.33      364994.073     1839743.934       365617.27
#Sta/Elev= 30
       0 1294.49    69.2 1286.81   118.6 1283.18   148.2 1280.36     168 1278.13
   177.9 1276.19   187.8 1275.44   207.6 1275.99   227.3 1274.44   247.1 1271.86
   276.7 1263.19   296.5 1255.02   306.4  1252.8   324.8 1244.35     336 1241.47
   345.9 1244.64   355.8 1247.56   395.3 1254.98   405.2 1255.61   415.1 1255.37
   444.8 1253.21   454.6 1252.98   464.5 1253.66   474.4  1255.2   513.9 1256.72
   563.4 1260.79   573.2 1261.11   602.9 1260.42   632.5 1261.84   672.1 1267.92
#Mann= 3 , 0 , 0
       0      .1       0   324.8    .045       0   345.9      .1       0
Bank Sta=324.8,345.9
XS Rating Curve= 0 ,0
Exp/Cntr=0.3,0.1

Type RM Length L Ch R = 1 ,39958.2 ,814.4,841.5,867
XS GIS Cut Line= 3
       1839115.2      365270.272     1839253.516      365550.171
     1839753.992      365685.224
#Sta/Elev= 30
       0 1264.69    29.3 1261.04    58.5 1255.04      78 1249.89    97.6 1246.79
   117.1 1241.54   126.8 1237.11   136.6 1236.34   146.4 1237.43   204.9  1239.1
   234.2 1237.08   292.7  1236.2   342.1 1238.99     362 1238.98     372  1237.2
     382 1233.39     392 1230.63   401.9 1230.29   411.9 1231.98   461.7 1235.72
   501.6 1235.99   511.6    1238   551.5 1240.72   561.4 1242.07   581.4 1246.81
   591.3 1247.85   720.9 1258.52   730.9 1259.72   800.7 1273.15   830.6 1277.17
#Mann= 3 , 0 , 0
       0      .1       0     382    .045       0   411.9      .1       0
Bank Sta=382,411.9
XS Rating Curve= 0 ,0
Exp/Cntr=0.3,0.1

Type RM Length L Ch R = 1 ,39116.6 ,400,389.6,379.2
XS GIS Cut Line= 2
     1838803.919      365699.242     1838966.027      366462.551
#Sta/Elev= 30
       0  1275.7    59.3 1253.38      79 1244.53    88.9 1243.69    98.8 1241.11
   167.9 1219.67   187.7  1217.1   227.2 1216.97   237.1 1215.83   257.3 1210.79
   266.7 1209.94   276.6 1210.67   306.2    1216   316.1 1216.86   355.6 1216.87
   375.4 1218.26   385.2 1220.23   395.1 1223.27   414.9 1231.02   464.2 1242.17
     484 1245.53   503.8 1246.22   523.5 1253.05   602.5 1277.09     642 1285.89
   721.1  1301.4   740.8 1306.51   750.7 1306.94   760.6 1310.67   780.3 1315.95
#Mann= 3 , 0 , 0
       0      .1       0   257.3    .045       0   276.6      .1       0
Bank Sta=257.3,276.6
XS Rating Curve= 0 ,0
Exp/Cntr=0.3,0.1

Type RM Length L Ch R = 1 ,38727   ,421.5,424.9,428.6
XS GIS Cut Line= 2
     1838308.376      365863.172     1838648.754      366293.339
#Sta/Elev= 30
       0  1322.4      20 1315.22    69.8 1295.99    79.8 1293.18    89.8 1292.03
    99.7 1289.24   119.7 1282.77   129.7  1280.9   149.6 1273.29   159.6  1269.1
   189.5 1253.96   199.5 1248.52   209.4 1241.93   229.4 1230.33   249.3 1221.64
   259.3 1217.68   269.3 1214.38   289.2 1209.03   299.2 1205.73   301.71205.345
   309.2  1204.2   316.91204.707   339.1 1207.64     369 1209.82   398.9 1211.25
   438.8  1215.7   468.8 1220.44   498.7 1225.78   528.6 1231.57   548.5 1236.04
#Mann= 3 , 0 , 0
       0      .1       0   301.7    .045       0   316.9      .1       0
Bank Sta=301.7,316.9
XS Rating Curve= 0 ,0
Exp/Cntr=0.3,0.1

Type RM Length L Ch R = 1 ,38302.1 ,550,549.5,547.7
XS GIS Cut Line= 2
     1837991.747      366076.618     1838301.989      366575.068
#Sta/Elev= 30
       0 1283.04      10 1279.18   119.4 1246.74   139.3 1239.06   179.1  1220.8
   189.1 1216.98     199 1214.78     209 1211.44   218.9 1208.93   228.9 1206.89
   238.8 1205.59   278.6 1202.81   288.6 1202.59   298.5 1203.39   328.4 1203.77
   338.3 1203.44   349.71201.707   358.2 1201.26   366.61201.328     408 1202.09
   427.9 1209.12   467.7 1221.39   487.6 1228.01   497.6 1232.26   507.5  1237.2
   537.4 1247.94   547.3 1252.44   557.3 1255.58   577.2 1257.24   587.1 1263.29
#Mann= 3 , 0 , 0
       0      .1       0   349.7    .045       0   366.6      .1       0
Bank Sta=349.7,366.6
XS Rating Curve= 0 ,0
Exp/Cntr=0.3,0.1

Type RM Length L Ch R = 1 ,37752.7 ,349.4,343,336.9
XS GIS Cut Line= 2
     1837571.413      366280.499     1837935.245      366822.753
#Sta/Elev= 30
       0 1288.56    29.7 1271.42    49.5 1264.04      89 1246.33    98.9 1243.24
   118.7  1239.8   128.6 1236.87   158.3 1224.28   168.2  1220.9   197.9 1213.42
   207.8 1208.48   217.7 1201.98   227.6 1194.18   236.21190.345   237.5 1189.76
   251.41190.313   267.1 1192.57   316.6 1193.86   366.1 1197.31   395.8 1197.06
   405.6 1197.86   415.6 1199.74   445.2 1208.11   544.2  1243.2     564 1248.03
   583.8 1248.18   603.5 1255.32   623.3 1261.03   643.1 1262.91     653 1265.54
#Mann= 3 , 0 , 0
       0      .1       0   236.2    .045       0   251.4      .1       0
Bank Sta=236.2,251.4
XS Rating Curve= 0 ,0
Exp/Cntr=0.3,0.1

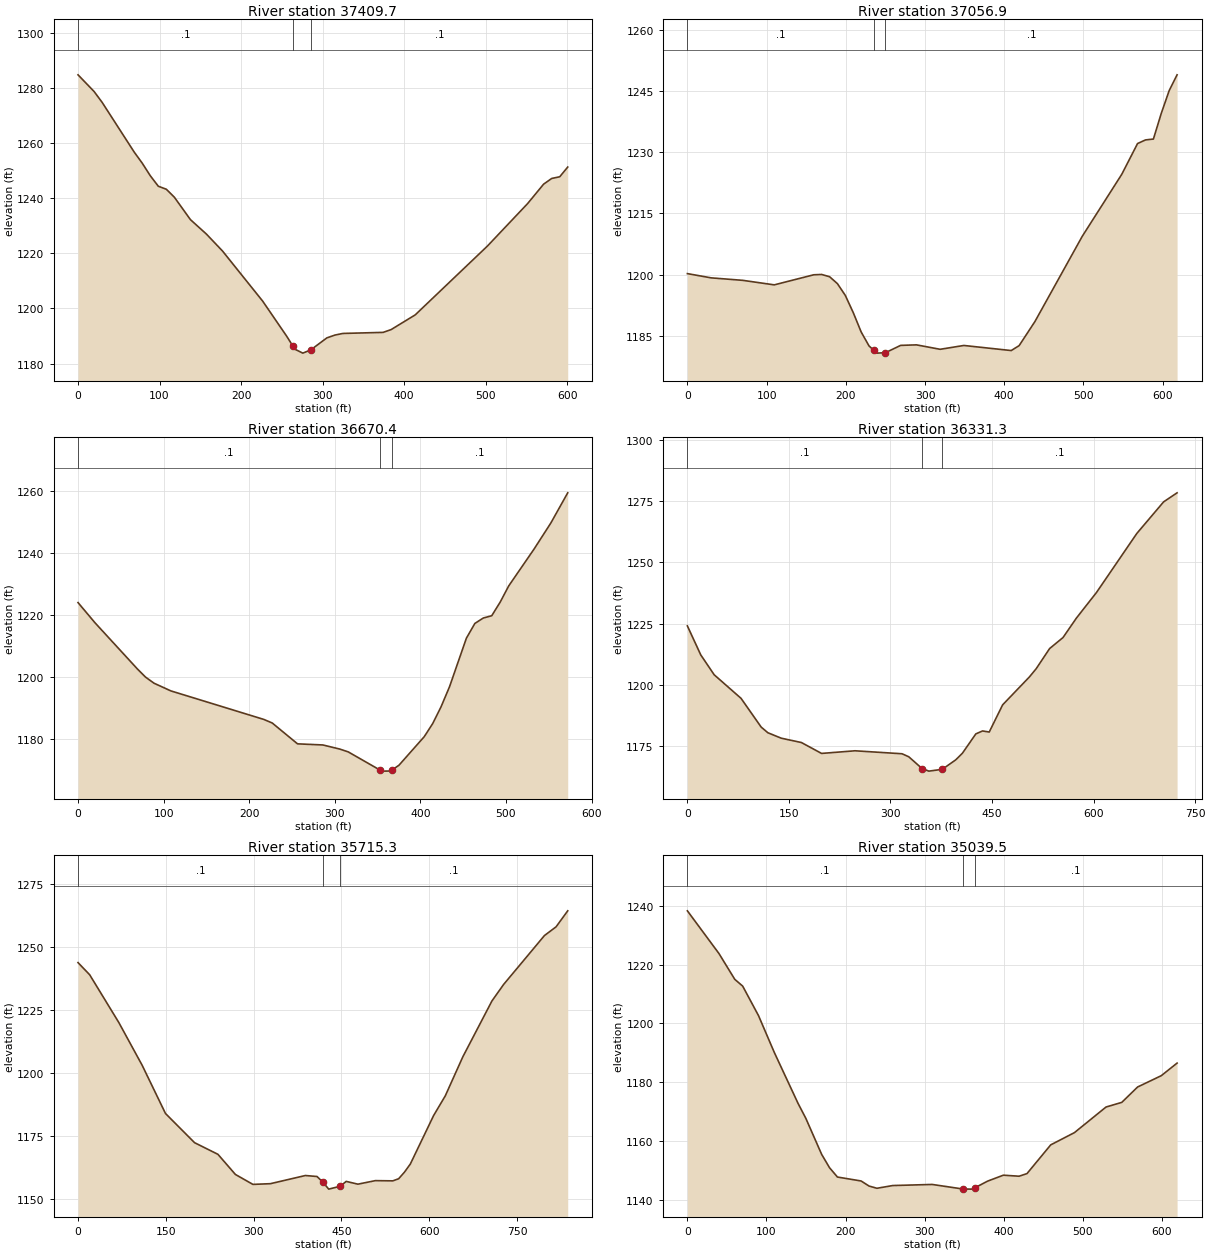
Type RM Length L Ch R = 1 ,37409.7 ,357.4,352.8,348.2
XS GIS Cut Line= 2
     1837255.767      366543.561     1837711.628      366934.911
#Sta/Elev= 30
       0 1284.68    19.7 1278.64    29.6 1274.69    68.9 1256.68    78.8 1252.64
    88.6 1248.11    98.5 1244.28   108.3  1243.2   118.2  1240.3   137.9 1232.18
   157.6 1226.91   177.3 1220.78   226.5 1202.64   256.1 1189.86   263.8 1186.21
   265.9 1185.21   275.8 1183.77   285.6 1184.95   305.3  1189.3   315.2 1190.32
     325 1190.91   374.3 1191.29   384.1  1192.3   413.7 1197.64   502.3  1222.6
   551.6    1238   571.2 1245.03   581.1  1247.1     591 1247.72   600.8 1251.24
#Mann= 3 , 0 , 0
       0      .1       0   263.8    .045       0   285.6      .1       0
Bank Sta=263.8,285.6
XS Rating Curve= 0 ,0
Exp/Cntr=0.3,0.1

Type RM Length L Ch R = 1 ,37056.9 ,401.6,386.5,371.1
XS GIS Cut Line= 2
     1837012.518      366863.006      1837552.56      367163.868
#Sta/Elev= 30
       0 1200.22    29.9 1199.18    69.8 1198.57   109.7 1197.46   159.5 1199.93
   169.5 1200.01   179.5 1199.46   189.4 1197.76   199.4 1194.86   209.4 1190.64
   219.4 1185.89   229.3 1182.47   235.1 1181.44   239.3  1180.7   250.1 1180.81
   269.2  1182.6   289.2 1182.73   319.1 1181.64     349 1182.58   408.8 1181.33
   418.8 1182.54   438.7 1188.44   498.5 1209.38   548.4 1224.61   568.3 1232.15
   578.3 1233.04   588.3 1233.25   598.2 1239.54   608.2 1245.13   618.2 1249.02
#Mann= 3 , 0 , 0
       0      .1       0   235.1    .045       0   250.1      .1       0
Bank Sta=235.1,250.1
XS Rating Curve= 0 ,0
Exp/Cntr=0.3,0.1

Type RM Length L Ch R = 1 ,36670.4 ,331.6,339.1,346.2
XS GIS Cut Line= 2
     1836996.441      367375.091      1837560.88      367281.138
#Sta/Elev= 30
       0 1223.95    19.7 1217.48    69.1 1202.62    78.9 1199.91    88.8 1197.94
   108.5 1195.46     217 1186.27   226.9 1185.11   256.5 1178.38   286.1 1178.02
   305.8  1176.7   315.7 1175.79   352.3 1170.01   355.2 1169.58     365 1169.61
   367.41170.059   374.9 1171.45   404.5 1180.68   414.4 1184.91   424.2 1190.34
   434.1 1196.82   453.8 1212.47   463.7 1217.23   473.6 1218.98   483.4 1219.71
   493.3 1224.11   503.2 1229.31   532.7 1241.15   552.5 1249.64   572.2 1259.36
#Mann= 3 , 0 , 0
       0      .1       0   352.3    .045       0   367.4      .1       0
Bank Sta=352.3,367.4
XS Rating Curve= 0 ,0
Exp/Cntr=0.3,0.1

Type RM Length L Ch R = 1 ,36331.3 ,630.8,616,601.2
XS GIS Cut Line= 2
     1836986.639      367593.542     1837700.933      367707.663
#Sta/Elev= 30
       0 1224.11    19.8 1212.29    39.6 1204.21    79.3  1194.6     109 1182.91
   118.9  1180.6   138.7 1178.38   168.4 1176.62   198.2 1172.18   247.7 1173.25
   317.1 1172.04     327 1170.82   346.8    1166   356.7 1164.97   376.5  1165.7
   396.4 1169.56   406.3 1172.27   426.1 1180.13     436 1181.33   445.9 1180.89
   465.7 1191.96   505.4 1203.37   515.3 1206.69   535.1 1214.88   554.9 1219.37
   574.7  1227.3   604.4 1237.74   663.9 1261.75   703.5 1274.62   723.4  1278.3
#Mann= 3 , 0 , 0
       0      .1       0   346.8    .045       0   376.5      .1       0
Bank Sta=346.8,376.5
XS Rating Curve= 0 ,0
Exp/Cntr=0.3,0.1

Type RM Length L Ch R = 1 ,35715.3 ,668.2,675.8,683.1
XS GIS Cut Line= 2
     1837111.639      368437.292     1837851.222      368046.667
#Sta/Elev= 30
       0 1243.84    19.9 1239.02    69.7 1220.06   109.5 1203.12   149.4 1183.96
   199.1 1172.37     239 1167.76   268.8 1159.77   298.7 1155.83   328.6 1156.11
   388.3 1159.35   408.2 1158.96   418.2  1156.7   428.2 1153.95   448.1 1155.12
     458 1157.02     478 1155.92   507.8 1157.32   537.7 1157.23   547.6 1158.07
   557.6  1160.7   567.6 1163.93   607.4 1183.18   627.3 1190.98   657.2 1206.44
     707 1228.64   726.9 1235.17   796.6 1254.57   816.5 1258.04   836.4 1264.39
#Mann= 3 , 0 , 0
       0      .1       0   418.2    .045       0   448.1      .1       0
Bank Sta=418.2,448.1
XS Rating Curve= 0 ,0
Exp/Cntr=0.3,0.1

Type RM Length L Ch R = 1 ,35039.5 ,331.5,332,332.5
XS GIS Cut Line= 2
     1837379.673      368846.246     1837991.625      368752.961
#Sta/Elev= 30
       0 1238.29    39.9 1223.77    59.9 1214.99    69.9 1212.68    89.9 1202.65
   109.8 1190.16   139.8 1172.84   149.8 1167.66   169.7 1155.46   179.7 1150.89
   189.7 1147.73   219.6 1146.39   229.6 1144.67   239.6 1143.91   259.6 1144.84
   309.5 1145.21   348.21143.663   359.4 1143.62   363.51144.081   379.4 1146.33
   399.4 1148.36   419.3 1148.01   429.3 1148.91   459.3 1158.68   489.2 1162.83
   529.2 1171.55   549.1 1173.13   569.1 1178.36     599 1182.21     619 1186.49
#Mann= 3 , 0 , 0
       0      .1       0   348.2    .045       0   363.5      .1       0
Bank Sta=348.2,363.5
XS Rating Curve= 0 ,0
Exp/Cntr=0.3,0.1

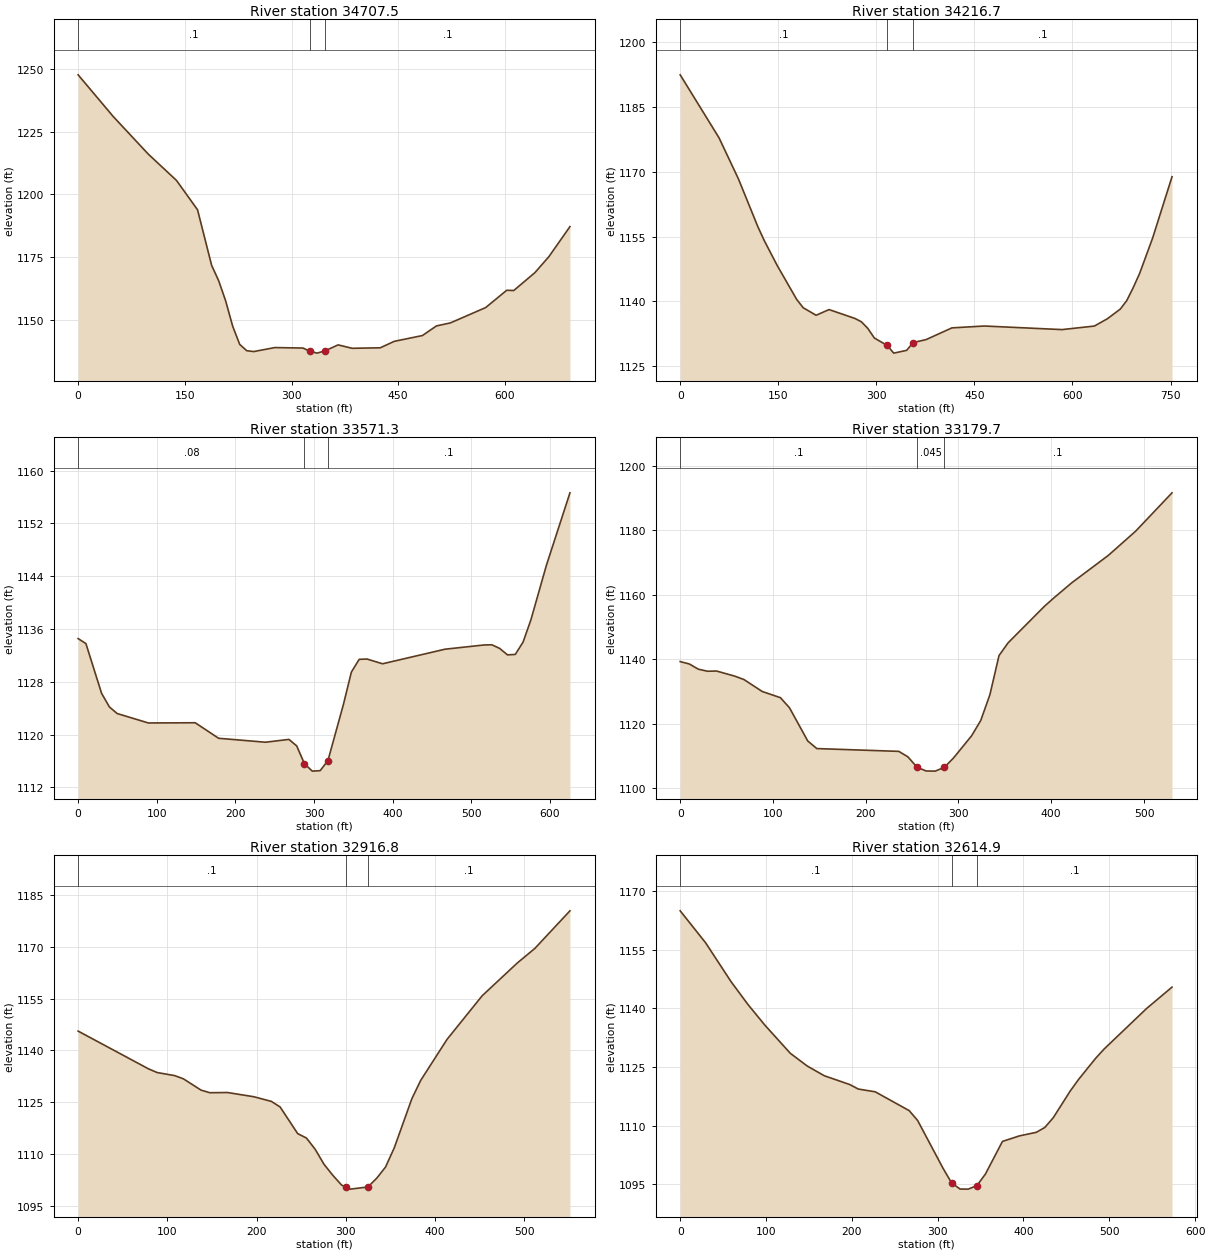
Type RM Length L Ch R = 1 ,34707.5 ,484.6,490.8,496.7
XS GIS Cut Line= 2
     1837370.136      369155.298     1838055.364      369062.381
#Sta/Elev= 30
       0 1247.77    49.4  1231.1    98.8 1216.05   138.3 1205.59   167.9 1193.86
   187.7 1171.67   197.6 1165.52   207.4 1157.49   217.3 1147.36   227.2 1140.08
   237.1 1137.56     247 1137.23   276.6 1138.82   316.1 1138.63     326 1137.36
   335.9  1136.6   347.31137.532   365.5 1139.89   385.3 1138.53   424.8 1138.73
   444.5 1141.31     484 1143.62   503.8 1147.46   523.6 1148.69     573  1154.8
   602.6 1161.71   612.5 1161.61   642.1 1168.72   661.9 1175.14   691.5 1187.13
#Mann= 3 , 0 , 0
       0      .1       0     326    .045       0   347.3      .1       0
Bank Sta=326,347.3
XS Rating Curve= 0 ,0
Exp/Cntr=0.3,0.1

Type RM Length L Ch R = 1 ,34216.7 ,630.7,645.4,659.9
XS GIS Cut Line= 2
     1837305.749      369517.031     1838052.224      369610.295
#Sta/Elev= 30
       0 1192.49    59.4  1177.9    89.1 1168.38   118.8 1157.31   128.7 1154.06
   148.5 1148.29   178.2 1140.46   188.1 1138.54   207.9 1136.79   227.7 1138.11
   267.3 1136.05   277.2 1135.28     287 1133.75     297 1131.52   316.8 1129.79
   326.6 1128.02   346.4 1128.66   356.3 1130.46   376.1 1131.15   415.7 1133.87
   465.2  1134.3     584 1133.47   633.5 1134.29   653.3 1135.97   673.1 1138.21
     683 1140.17   692.9 1143.17   702.8  1146.5   722.6 1154.66   752.3 1168.88
#Mann= 3 , 0 , 0
       0      .1       0   316.8    .045       0   356.3      .1       0
Bank Sta=316.8,356.3
XS Rating Curve= 0 ,0
Exp/Cntr=0.3,0.1

Type RM Length L Ch R = 1 ,33571.3 ,388.8,391.7,394.5
XS GIS Cut Line= 2
        1837151.      369853.437     1837614.149      370273.482
#Sta/Elev= 30
       0 1134.54     9.9 1133.78    29.8 1126.25    39.7 1124.19    49.6 1123.18
    89.3 1121.75   148.9 1121.78   178.6 1119.43   238.2 1118.83     268 1119.26
   277.9 1118.27   287.8 1115.56   297.7 1114.45   307.7 1114.52   317.6 1116.04
   337.4 1124.61   347.4 1129.46   357.3 1131.39   367.2 1131.44   387.1 1130.72
   466.5 1132.93   516.1 1133.57     526  1133.6   535.9 1133.05   545.9 1132.07
   555.8 1132.14   565.7 1134.01   575.6 1137.36   595.5  1145.7   625.3 1156.63
#Mann= 3 , 0 , 0
       0     .08       0   287.8    .045       0   317.6      .1       0
Bank Sta=287.8,317.6
XS Rating Curve= 0 ,0
Exp/Cntr=0.3,0.1

Type RM Length L Ch R = 1 ,33179.7 ,271.8,262.9,253.8
XS GIS Cut Line= 2
     1836933.715      370135.332     1837286.353      370531.321
#Sta/Elev= 30
       0  1139.3     9.8 1138.57    19.6 1136.94    29.5 1136.31    39.3 1136.37
    58.9 1134.78    68.7 1133.74    88.4 1130.03     108 1128.11   117.8 1124.98
   137.5 1114.67   147.3 1112.31   235.7 1111.44   245.5 1109.74   255.3 1106.52
   265.1 1105.36   274.9 1105.31   284.8 1106.49   294.6 1109.37   314.2  1116.3
     324 1121.02   333.9 1129.05   343.7 1141.18   353.5 1145.13   392.8  1156.5
   402.6 1159.01   422.2 1163.78   461.5 1172.25     491 1179.78   530.2 1191.68
#Mann= 3 , 0 , 0
       0      .1       0   255.3    .045       0   284.8      .1       0
Bank Sta=255.3,284.8
XS Rating Curve= 0 ,0
Exp/Cntr=0.3,0.1

Type RM Length L Ch R = 1 ,32916.8 ,301.9,301.9,301.9
XS GIS Cut Line= 2
     1836677.717      370401.585      1837173.04      370643.645
#Sta/Elev= 30
       0  1145.6    78.8 1134.68    88.6  1133.6   108.3 1132.71   118.1 1131.77
   137.8 1128.51   147.7 1127.76   167.4 1127.82   196.9  1126.6   216.6 1125.25
   226.4 1123.64   246.1 1115.93     256 1114.62   265.8 1111.35   275.6 1107.05
   285.5 1103.85   295.3 1101.03     3001100.472   305.2 1099.85   324.9 1100.48
   334.7 1103.01   344.6 1106.25   354.4 1111.83   374.1 1126.03     384 1131.33
   413.5  1143.2   452.9 1155.83   492.2  1165.3   511.9 1169.52   551.3 1180.42
#Mann= 3 , 0 , 0
       0      .1       0     300    .045       0   324.9      .1       0
Bank Sta=300,324.9
XS Rating Curve= 0 ,0
Exp/Cntr=0.3,0.1

Type RM Length L Ch R = 1 ,32614.9 ,283.6,262.5,241.3
XS GIS Cut Line= 2
     1836519.979       370660.26     1837034.859      370911.878
#Sta/Elev= 30
       0 1164.91    29.6 1156.75    59.3  1146.8      79 1140.96    98.8 1135.66
   128.4 1128.48   148.2 1125.22     168 1122.75   197.6 1120.51   207.5 1119.36
   227.2 1118.66   266.8 1113.85   276.7 1111.32   306.3  1099.1   316.2 1095.39
   326.1  1093.8   335.7 1093.78   345.8  1094.7   355.7 1097.64   375.5 1105.97
   395.2 1107.38     415  1108.3   424.9 1109.54   434.8 1112.06   454.5 1118.86
   464.4 1121.87   484.2 1127.24     494 1129.59   543.4 1139.93   573.1 1145.41
#Mann= 3 , 0 , 0
       0      .1       0   316.2    .045       0   345.8      .1       0
Bank Sta=316.2,345.8
XS Rating Curve= 0 ,0
Exp/Cntr=0.3,0.1

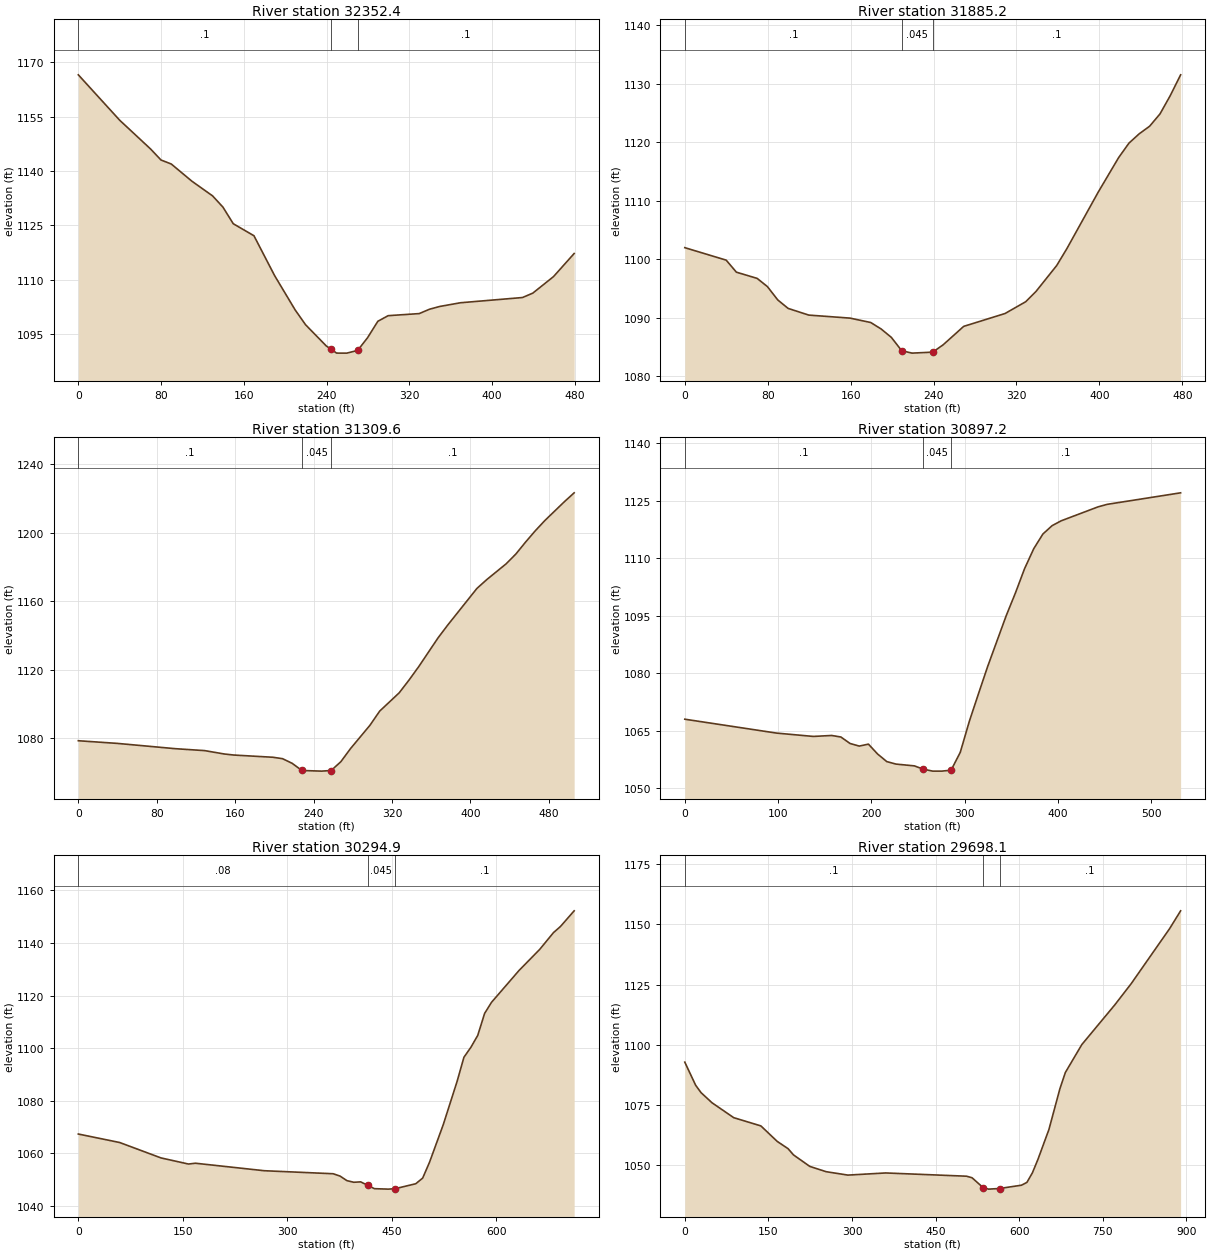
Type RM Length L Ch R = 1 ,32352.4 ,462.4,467.2,472
XS GIS Cut Line= 2
     1836514.498      371161.344     1836943.427      370947.321
#Sta/Elev= 30
       0 1166.51      40 1153.99    69.9 1146.05    79.9 1143.03    89.9 1141.91
   109.8 1137.18   129.8 1133.13   139.8 1130.04   149.8 1125.45   169.8 1122.14
   189.8 1111.13   209.7 1101.66   219.7  1097.6   239.7 1091.76   244.31090.849
   249.7 1089.78   255.1 1089.77   259.6 1089.77   270.1 1090.52   279.6    1094
   289.6 1098.55   299.6  1100.1   329.6 1100.67   339.6 1101.88   349.5 1102.64
   369.5 1103.66   429.4  1105.1   439.4 1106.31   459.4 1110.86   479.4 1117.24
#Mann= 3 , 0 , 0
       0      .1       0   244.3    .045       0   270.1      .1       0
Bank Sta=244.3,270.1
XS Rating Curve= 0 ,0
Exp/Cntr=0.3,0.1

Type RM Length L Ch R = 1 ,31885.2 ,562.6,575.6,588.6
XS GIS Cut Line= 2
     1836756.034      371504.814     1837219.256      371385.277
#Sta/Elev= 30
       0 1101.99    39.9 1099.86    49.8  1097.8    69.8 1096.74    79.7 1095.34
    89.7 1093.06    99.7 1091.61   119.6 1090.47   159.5 1089.95   179.4  1089.2
   189.4  1088.1   199.3 1086.66   209.3 1084.38   219.3 1083.97   239.2 1084.14
   249.2 1085.38   269.1 1088.54     309 1090.74   328.9 1092.75   338.9 1094.52
   358.8 1098.93   368.8 1101.87   398.7 1111.42   418.6 1117.38   428.6 1119.86
   438.5 1121.45   448.5 1122.74   458.5 1124.84   468.4 1127.97   478.4 1131.52
#Mann= 3 , 0 , 0
       0      .1       0   209.3    .045       0   239.2      .1       0
Bank Sta=209.3,239.2
XS Rating Curve= 0 ,0
Exp/Cntr=0.3,0.1

Type RM Length L Ch R = 1 ,31309.6 ,405.1,412.4,419.7
XS GIS Cut Line= 2
     1836773.361      371944.132     1837253.351      372103.665
#Sta/Elev= 30
       0 1078.38    39.7 1076.83    99.2 1073.72   128.9  1072.6   148.8 1070.64
   158.7 1070.01   198.4 1068.72   208.3 1067.89   218.2 1065.15   228.1 1060.98
     248 1060.61   257.9 1060.97   267.8 1066.12   277.7  1073.8   297.5 1087.43
   307.4 1095.69   327.3 1106.38   337.2 1113.75   347.1 1121.58     367 1138.56
   376.9 1146.07   406.6 1167.43   416.6 1172.58   436.4 1181.82   446.3 1187.53
   456.2 1194.51   466.1 1201.11     476 1207.19   495.9 1218.18   505.8 1223.34
#Mann= 3 , 0 , 0
       0      .1       0   228.1    .045       0   257.9      .1       0
Bank Sta=228.1,257.9
XS Rating Curve= 0 ,0
Exp/Cntr=0.3,0.1

Type RM Length L Ch R = 1 ,30897.2 ,598.9,602.3,605.8
XS GIS Cut Line= 2
      1836619.44      372234.511     1837044.211      372554.329
#Sta/Elev= 30
       0 1067.96    98.5 1064.33   137.8 1063.46   157.5 1063.71   167.4 1063.31
   177.2 1061.62   187.1 1060.94   196.9 1061.45   206.8 1058.86   216.6 1056.89
   226.5 1056.24   246.2 1055.77   255.61054.919   265.8  1054.4   275.7  1054.4
   285.6 1054.65   295.4 1059.31   305.2 1067.47   315.1 1074.74   324.9 1081.81
   344.6 1094.95   354.5  1100.9   364.3 1107.24   374.2 1112.49     384 1116.32
   393.9 1118.51   403.7 1119.78   443.1 1123.41   452.9 1124.07   531.7 1127.08
#Mann= 3 , 0 , 0
       0      .1       0   255.6    .045       0   285.6      .1       0
Bank Sta=255.6,285.6
XS Rating Curve= 0 ,0
Exp/Cntr=0.3,0.1

Type RM Length L Ch R = 1 ,30294.9 ,609.6,596.8,584.1
XS GIS Cut Line= 2
     1836188.301      372603.603     1836726.022       373069.65
#Sta/Elev= 30
       0 1067.33    59.3 1064.11   118.6 1058.25   158.1 1055.92     168 1056.23
   266.8 1053.38   365.7 1052.23   375.6 1051.34   385.4 1049.62   395.3 1048.99
   405.2 1049.14   415.1 1047.85     425 1046.55   444.7 1046.38   454.6 1046.54
   484.3 1048.43   494.2 1050.58     504 1056.58   523.8 1070.95   543.6 1087.35
   553.4 1096.52   563.3 1100.28   573.2 1104.82   583.1 1113.21     593 1117.42
   632.5 1129.53   662.2 1137.55   681.9 1143.92   691.8 1146.21   711.6 1152.21
#Mann= 3 , 0 , 0
       0     .08       0   415.1    .045       0   454.6      .1       0
Bank Sta=415.1,454.6
XS Rating Curve= 0 ,0
Exp/Cntr=0.3,0.1

Type RM Length L Ch R = 1 ,29698.1 ,850.7,848,844.7
XS GIS Cut Line= 4
     1835828.863      373112.347     1836113.823      373261.865
     1836166.123      373396.351     1836579.269      373489.009
#Sta/Elev= 30
       0 1092.76    19.5 1083.15    29.2 1080.08    48.8 1075.88    87.8 1069.68
   136.5 1066.26   165.8 1059.82   185.3 1056.79     195 1054.21   224.3 1049.42
   253.5 1047.23   292.6 1045.81   360.3  1046.7   505.5 1045.35   515.3 1044.71
     535 1040.65   544.9 1039.98   564.6 1040.24     604 1041.61   613.8 1042.79
   623.6 1046.76   633.5 1052.32   653.2 1064.74   672.9 1081.68   682.7 1088.45
   712.3 1100.08   771.4 1116.56   800.9 1125.41   869.8 1148.27   889.5 1155.66
#Mann= 3 , 0 , 0
       0      .1       0     535    .045       0   564.6      .1       0
Bank Sta=535,564.6
XS Rating Curve= 0 ,0
Exp/Cntr=0.3,0.1