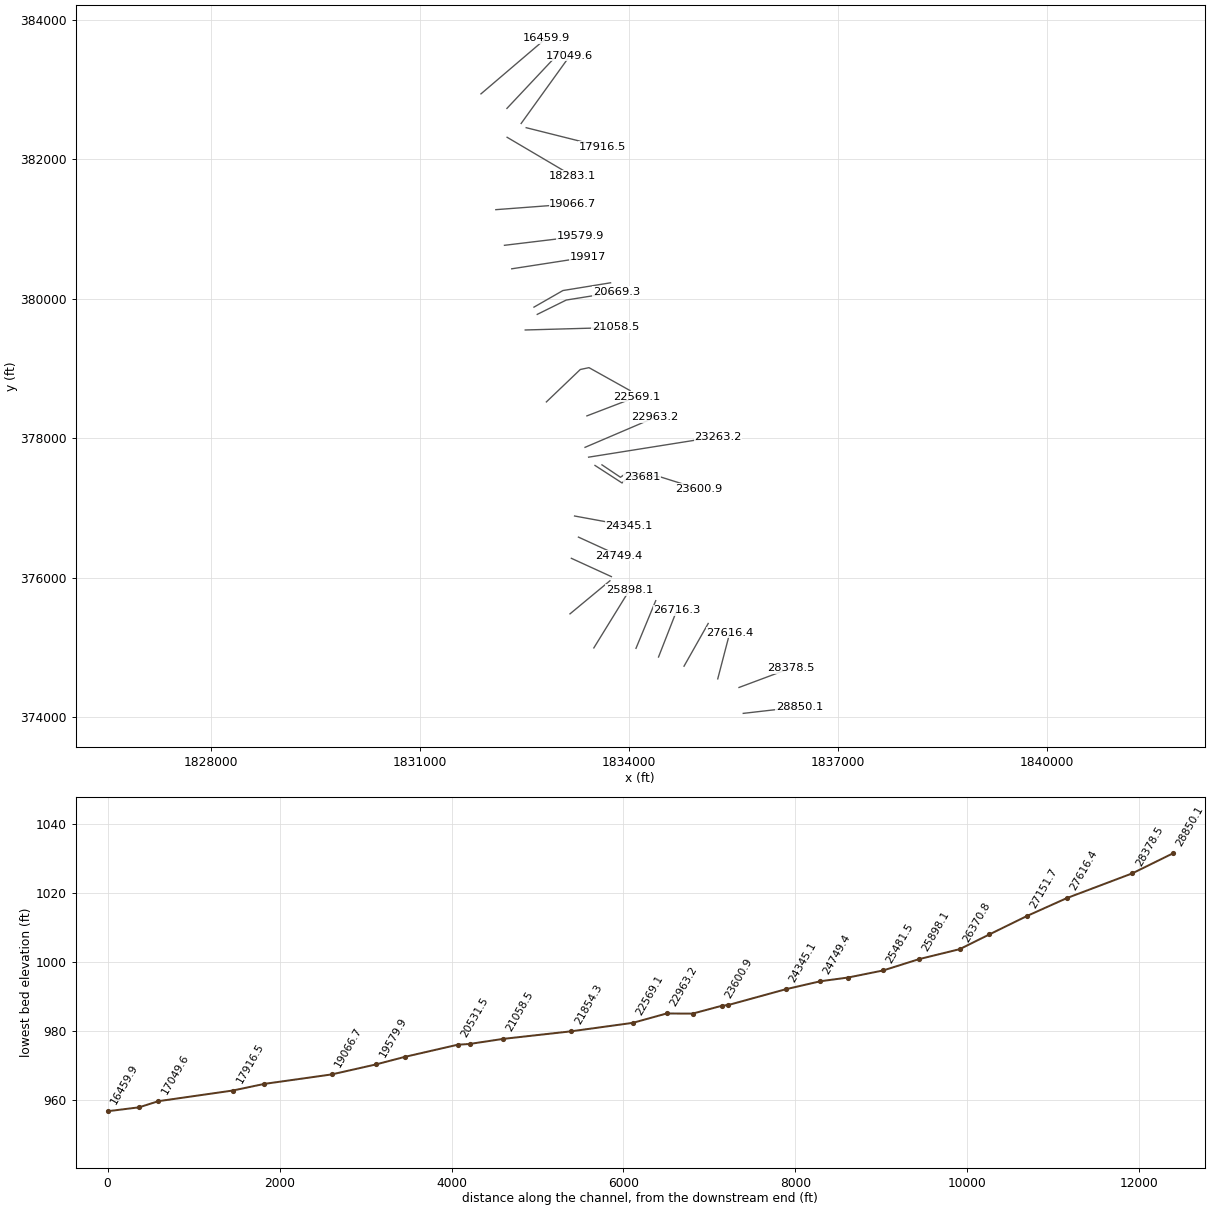
HEC-RAS study BoothsCk.prj: BoothsCk

--- BoothsCk.g01 (geometry) --- (continued)

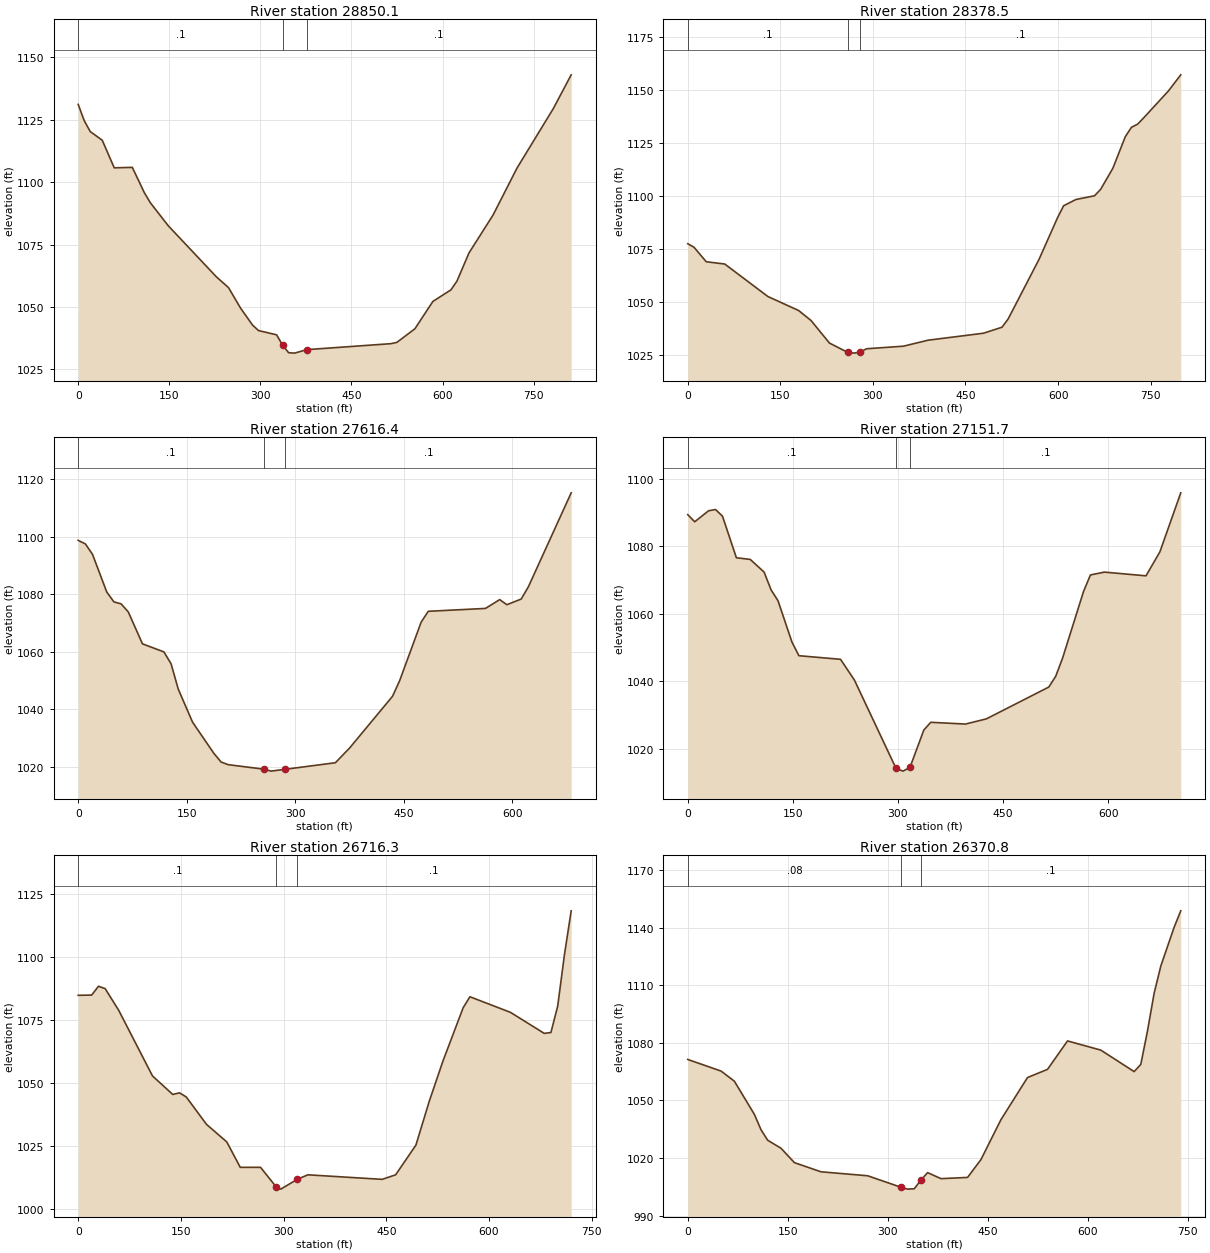
Type RM Length L Ch R = 1 ,28850.1 ,465.7,471.5,477.4
XS GIS Cut Line= 2
     1835638.417      374057.294     1836444.903      374149.947
#Sta/Elev= 30
       0 1131.13     9.9 1124.65    19.8 1120.25    39.6 1116.78    59.4 1105.72
    89.1 1105.91   108.9  1095.8   118.8 1091.75   148.5 1082.48   227.7 1062.05
   247.5 1057.78   267.3 1049.59   287.1 1042.77     297 1040.57   326.7 1038.87
   336.6 1034.73   346.5 1031.71   356.4 1031.54   376.2 1032.93   514.8 1035.32
   524.7 1035.83   554.4 1041.27   584.1 1052.25   613.8 1056.87   623.7 1060.37
   643.5 1071.65   683.1 1086.81   722.7 1105.68   782.1 1129.34   811.8 1142.96
#Mann= 3 , 0 , 0
       0      .1       0   336.6    .045       0   376.2      .1       0
Bank Sta=336.6,376.2
XS Rating Curve= 0 ,0
Exp/Cntr=0.3,0.1

Type RM Length L Ch R = 1 ,28378.5 ,741,762.1,782.8
XS GIS Cut Line= 2
     1835577.206      374428.641     1836325.459      374708.128
#Sta/Elev= 30
       0 1077.35      10 1075.73      30 1068.85    59.9 1067.78   129.8 1052.46
   179.7 1045.84   199.7 1041.15   229.6  1030.5   258.9 1026.15   269.6 1025.75
   279.6 1026.29   289.6 1027.81   349.4 1029.02   389.4 1031.85   479.2 1035.14
   509.2 1037.97   519.2 1041.91   569.1 1069.95   599.1 1089.59     609 1095.27
     629 1098.22     659 1099.96     669 1103.01   688.9 1113.02   708.9 1127.83
   718.9 1132.26   728.9 1133.75   738.8 1136.75   778.8 1149.41   798.8 1157.02
#Mann= 3 , 0 , 0
       0      .1       0   258.9    .045       0   279.6      .1       0
Bank Sta=258.9,279.6
XS Rating Curve= 0 ,0
Exp/Cntr=0.3,0.1

Type RM Length L Ch R = 1 ,27616.4 ,470.6,464.7,459.3
XS GIS Cut Line= 2
     1835272.168      374552.012     1835444.371      375211.518
#Sta/Elev= 30
       0 1098.66     9.9 1097.44    19.8 1093.82    39.5 1080.73    49.4 1077.31
    59.3 1076.63    69.2 1073.85    88.9 1062.74   118.5 1059.95   128.4 1055.84
   138.3 1047.07   158.1 1035.57   187.7  1024.7   197.6 1021.73   207.4 1020.81
   256.8 1019.25   266.7 1018.57   286.5 1019.22   355.6 1021.48   375.4 1026.64
   434.6 1044.55   444.5 1050.01   474.2  1070.3     484 1074.04   563.1 1075.04
   582.8  1078.1   592.7 1076.33   612.5 1078.29   622.4 1082.54   681.6 1115.16
#Mann= 3 , 0 , 0
       0      .1       0   256.8    .045       0   286.5      .1       0
Bank Sta=256.8,286.5
XS Rating Curve= 0 ,0
Exp/Cntr=0.3,0.1

Type RM Length L Ch R = 1 ,27151.7 ,431.8,435.5,438.4
XS GIS Cut Line= 2
     1834788.333       374733.91     1835135.017      375346.108
#Sta/Elev= 30
       0 1089.37     9.9 1087.26    29.7 1090.52    39.6  1090.9    49.6 1088.91
    69.4  1076.6    89.2  1076.1     109 1072.34   118.9 1067.08   128.8 1063.87
   148.6 1051.66   158.6 1047.57     218  1046.5   237.8 1040.37   297.3 1014.15
   307.2 1013.36   317.1 1014.46   336.9 1025.53   346.8 1027.83   396.4 1027.31
   426.1 1028.84   515.3 1038.28   525.2  1041.5   535.1 1046.96   564.8 1066.58
   574.7  1071.5   594.6 1072.34     654 1071.24   673.8 1078.34   703.6 1095.84
#Mann= 3 , 0 , 0
       0      .1       0   297.3    .045       0   317.1      .1       0
Bank Sta=297.3,317.1
XS Rating Curve= 0 ,0
Exp/Cntr=0.3,0.1

Type RM Length L Ch R = 1 ,26716.3 ,346.1,345.5,345.3
XS GIS Cut Line= 2
     1834422.543      374865.221     1834684.884      375535.761
#Sta/Elev= 30
       0 1084.98    19.7 1085.06    29.6 1088.57    39.4 1087.63    59.2 1079.01
   108.5 1052.98   138.1 1045.62     148 1046.26   157.8 1044.63   187.4 1033.75
     217 1026.79   236.7 1016.69   266.3  1016.7   289.4 1008.84   295.9 1008.04
   319.71011.893   335.4 1013.72   443.9 1011.92   463.6 1013.72   493.2  1025.5
   512.9 1043.07   532.6 1058.79   562.2 1080.03   572.1  1084.4   631.3 1078.21
   680.6 1069.87   690.4  1070.2   700.3  1080.7   710.2 1101.19     720 1118.51
#Mann= 3 , 0 , 0
       0      .1       0   289.4    .045       0   319.7      .1       0
Bank Sta=289.4,319.7
XS Rating Curve= 0 ,0
Exp/Cntr=0.3,0.1

Type RM Length L Ch R = 1 ,26370.8 ,476,472.7,468.7
XS GIS Cut Line= 2
     1834099.261      374990.043     1834382.209      375673.093
#Sta/Elev= 30
       0 1071.34      50 1065.28    69.9 1060.01    99.9 1042.72   109.9 1034.68
   119.9 1029.23   139.9 1025.05   159.9 1017.57   199.8 1012.79   269.8 1010.72
   319.7 1004.74   329.7 1003.76   339.7 1003.96   349.7 1008.49   359.7 1012.35
   379.7 1009.22   419.6 1009.86   439.6 1019.12   469.6 1039.92   509.5 1061.92
   539.5 1066.18   569.5    1081   619.4 1076.21   669.4 1065.01   679.4 1068.79
   689.4 1086.18   699.4 1105.89   709.4 1120.04   729.3 1140.18   739.3  1148.8
#Mann= 3 , 0 , 0
       0     .08       0   319.7    .045       0   349.7      .1       0
Bank Sta=319.7,349.7
XS Rating Curve= 0 ,0
Exp/Cntr=0.3,0.1

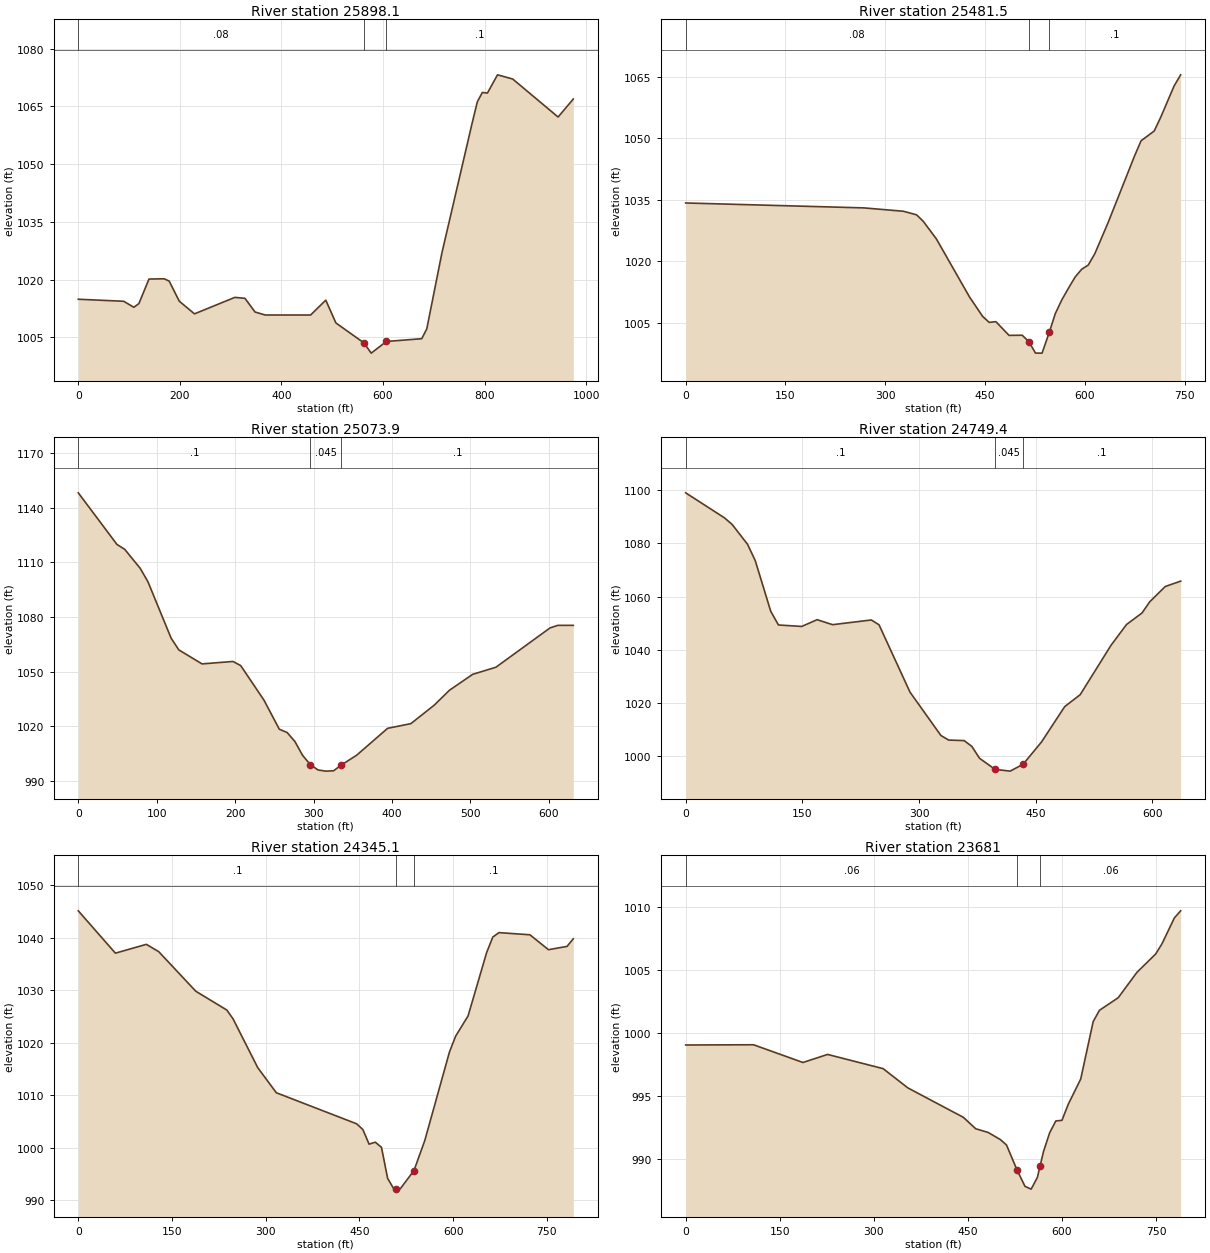
Type RM Length L Ch R = 1 ,25898.1 ,424.1,416.7,409.1
XS GIS Cut Line= 2
     1833494.257      374995.981     1834006.017      375825.585
#Sta/Elev= 30
       0 1014.88    89.5 1014.35   109.4 1012.79   119.4 1013.75   139.2 1020.13
   169.1 1020.19     179  1019.6   198.9 1014.37   228.8 1011.08   308.3 1015.36
   328.2 1015.12   348.1 1011.56     368 1010.78   457.5 1010.78   487.4 1014.64
   507.3 1008.72   562.41003.541   576.9 1000.87   606.7  1003.9   676.4 1004.62
   686.3 1007.18   716.1 1026.93   775.8 1060.77   785.8 1066.19   795.7 1068.63
   805.7 1068.48   825.6 1073.22   855.4 1072.14   944.9 1062.25   974.8 1066.93
#Mann= 3 , 0 , 0
       0     .08       0   562.4    .045       0   606.7      .1       0
Bank Sta=562.4,606.7
XS Rating Curve= 0 ,0
Exp/Cntr=0.3,0.1

Type RM Length L Ch R = 1 ,25481.5 ,433.1,407.6,381.9
XS GIS Cut Line= 2
     1833152.194      375483.991     1833725.087      375958.471
#Sta/Elev= 30
       0 1034.24   267.8 1033.04   327.3 1032.22   347.1 1031.34   357.1 1029.76
   376.9 1025.44   426.5 1011.32   446.3 1006.56   456.2 1005.09   466.2 1005.27
     486 1001.92   505.8 1001.96   515.8 1000.38   525.7   997.6   535.6  997.59
   546.7 1002.78   555.4  1007.2   565.3  1010.6   575.3 1013.44   585.2 1016.14
   595.1 1018.06     605 1019.08   614.9 1021.86   634.8 1029.43   674.4 1045.64
   684.4 1049.42   704.2 1051.82   714.1 1055.22     734 1062.79   743.9 1065.52
#Mann= 3 , 0 , 0
       0     .08       0   515.8    .045       0   546.7      .1       0
Bank Sta=515.8,546.7
XS Rating Curve= 0 ,0
Exp/Cntr=0.3,0.1

Type RM Length L Ch R = 1 ,25073.9 ,324.4,324.5,324.5
XS GIS Cut Line= 2
     1833171.889      376280.378     1833746.052      376018.012
#Sta/Elev= 30
       0 1148.05    49.3 1119.78    59.2 1117.09    78.9 1106.72    88.8 1099.36
   118.4  1068.4   128.2 1061.99   157.8  1054.3   197.3 1055.64   207.1 1053.39
   236.7 1034.52   256.4  1018.5   266.3 1016.72   276.2 1011.83     286 1004.24
   295.9  999.11   305.8  996.17   315.6  995.54   325.5  995.71   335.4  998.86
   355.1 1004.29   394.5    1019   424.1 1021.55   453.7  1031.6   473.4 1039.87
     503 1048.59   532.6 1052.47   601.7 1074.03   611.5 1075.42   631.3 1075.43
#Mann= 3 , 0 , 0
       0      .1       0   295.9    .045       0   335.4      .1       0
Bank Sta=295.9,335.4
XS Rating Curve= 0 ,0
Exp/Cntr=0.3,0.1

Type RM Length L Ch R = 1 ,24749.4 ,398.9,404.3,409.9
XS GIS Cut Line= 2
     1833273.508      376584.476     1833852.372      376319.962
#Sta/Elev= 30
       0 1098.99    49.7 1089.63    59.7 1087.13    79.6 1079.64    89.5  1073.5
   109.4 1054.47   119.3 1049.35   149.2  1048.8     169 1051.34   188.9 1049.46
   238.7 1051.23   248.6 1049.42   288.4 1024.13   328.2 1007.82   338.1 1006.12
     358 1005.92   367.9 1003.75   377.9  999.25   397.8  995.11   417.2  994.45
   433.8997.0226   457.4 1005.36   487.3 1018.68   507.2 1023.16   546.9 1041.74
   566.8 1049.53   586.7 1053.85   596.7 1058.08   616.6  1063.8   636.4 1065.82
#Mann= 3 , 0 , 0
       0      .1       0   397.8    .045       0   433.8      .1       0
Bank Sta=397.8,433.8
XS Rating Curve= 0 ,0
Exp/Cntr=0.3,0.1

Type RM Length L Ch R = 1 ,24345.1 ,633.3,664.1,692.2
XS GIS Cut Line= 2
     1833217.974      376887.009     1833997.152      376744.227
#Sta/Elev= 30
       0  1045.1    59.4 1037.04   108.9 1038.72   128.7 1037.33   188.1 1029.79
   237.6 1026.22   247.6 1024.55   287.2 1015.25   316.9 1010.47   445.6 1004.55
   455.5 1003.45   465.4 1000.68   475.3 1001.06   485.2 1000.08   495.1  994.17
     505  992.16   508.9992.1405   514.9  992.12   537.2995.6493   554.5 1001.36
   594.1 1018.25     604 1021.26   623.8 1025.09   653.5 1037.14   663.4 1040.11
   673.3 1040.95   722.8 1040.54   752.5  1037.7   782.2 1038.33   792.2 1039.78
#Mann= 3 , 0 , 0
       0      .1       0   508.9    .045       0   537.2      .1       0
Bank Sta=508.9,537.2
XS Rating Curve= 0 ,0
Exp/Cntr=0.3,0.1

Type RM Length L Ch R = 1 ,23681   ,91.7,80.1,70.8
XS GIS Cut Line= 4
     1833510.708      377612.073     1833898.957      377360.699
     1833999.213      377454.844     1834188.252      377445.907
#Sta/Elev= 30
       0  999.03   108.2  999.05     187  997.64   226.3  998.28   314.9  997.15
   354.3  995.62   442.8  993.28   462.5  992.37   482.2  992.08   501.8  991.51
   511.6  991.08   528.5989.0786   541.1  987.79   550.9  987.57   560.8   988.5
   565.3989.4459   570.6  990.56   580.4  992.05   590.2  992.99     600  993.04
     610  994.31   629.9  996.32   649.8 1000.89   659.8 1001.79   689.7 1002.79
   719.6 1004.81   749.5 1006.27   759.4 1007.07   779.3 1009.14   789.3  1009.7
#Mann= 3 , 0 , 0
       0     .06       0   528.5    .045       0   565.3     .06       0
Bank Sta=528.5,565.3
XS Rating Curve= 0 ,0
Exp/Cntr=0.3,0.1

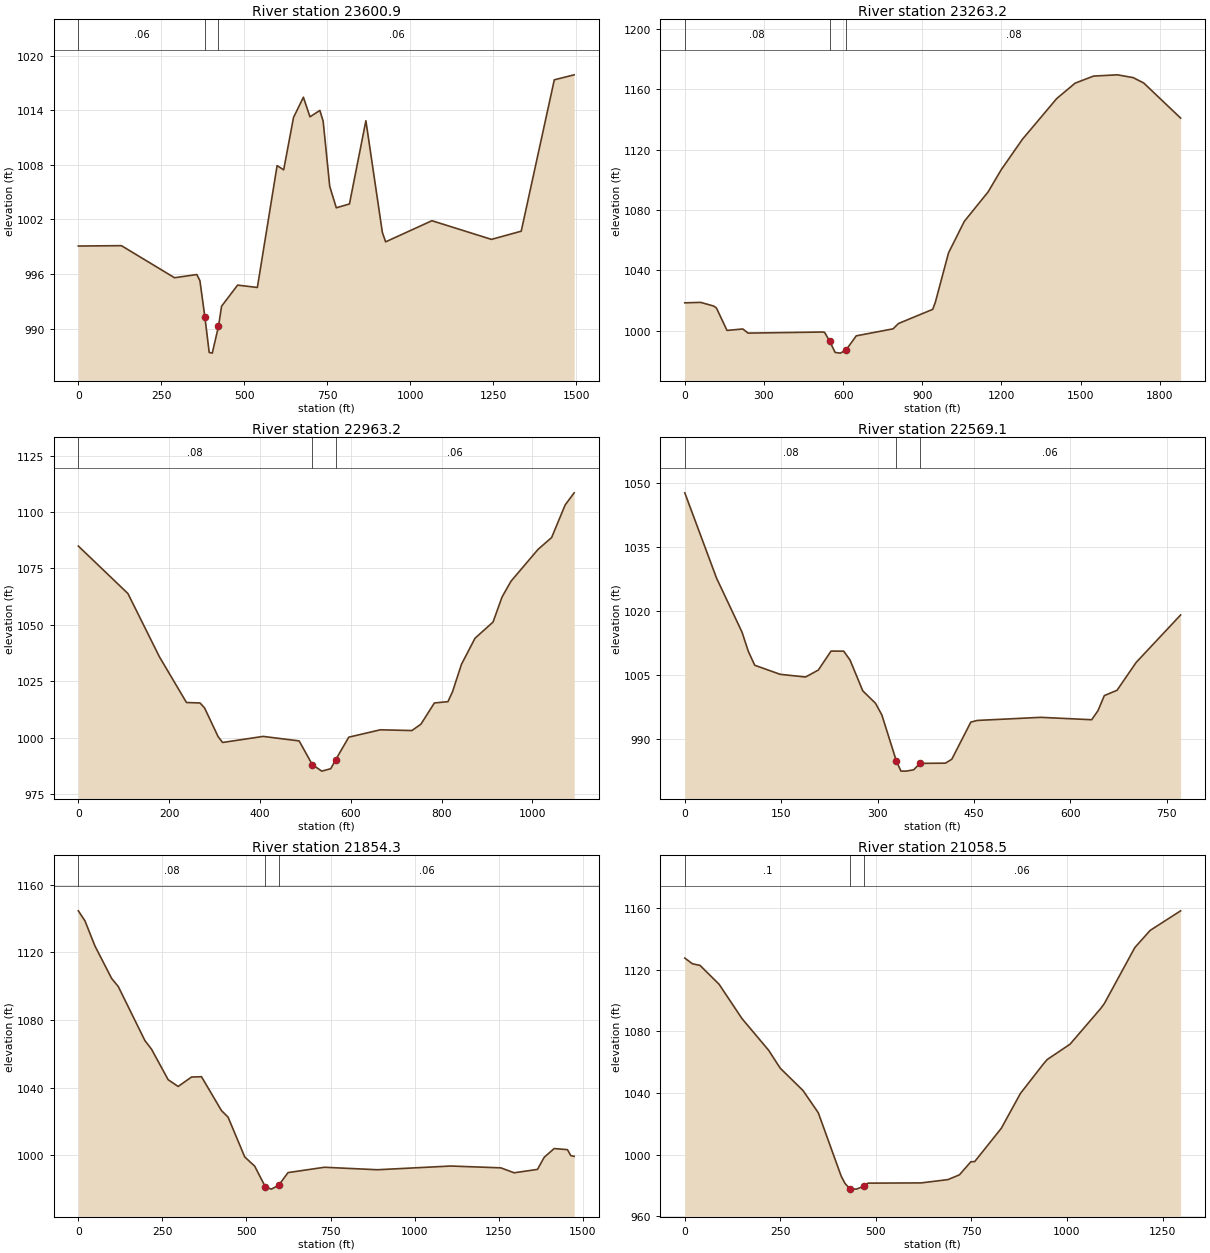
Type RM Length L Ch R = 1 ,23600.9 ,348.5,337.7,326.5
XS GIS Cut Line= 5
     1833610.879       377620.42     1833876.331      377442.357
     1833982.401      377518.157     1834452.423       377446.59
     1834994.012      377276.377
#Sta/Elev= 30
       0  999.08   129.8  999.12   289.7   995.6   356.9  995.95   366.2  995.27
     381991.3212   394.1   987.4   403.4  987.32   422.1  990.27   431.4  992.47
   479.7  994.79   539.2  994.53   598.6 1007.91   618.4 1007.45   648.1  1013.2
   677.8 1015.42   697.6 1013.27   727.4 1013.97   737.3 1012.79   757.1 1005.63
   776.9 1003.28   816.5  1003.7     866 1012.84   915.6 1000.58   925.4  999.54
  1064.9 1001.86  1244.2  999.81  1333.8 1000.71  1433.4 1017.33  1493.2 1017.88
#Mann= 3 , 0 , 0
       0     .06       0     381    .045       0   422.1     .06       0
Bank Sta=381,422.1
XS Rating Curve= 0 ,0
Exp/Cntr=0.3,0.1

Type RM Length L Ch R = 1 ,23263.2 ,294.2,300,306
XS GIS Cut Line= 2
     1833419.189      377730.584     1835274.651      378025.933
#Sta/Elev= 30
       0  1018.4      60 1018.71   109.9 1016.25   119.9    1015   159.9 1000.11
   219.9 1001.07   239.8  998.33   519.7  999.05   529.7  998.86   549.2992.8645
   569.6  985.53   589.6  985.06   611.5987.2333   649.6  996.52   789.5 1001.18
   809.5 1004.69   939.4 1014.08   949.4 1018.82   999.4 1051.56  1059.3 1072.46
  1149.3 1091.94  1199.2 1106.71  1279.2 1126.82  1409.1 1153.81  1479.1 1164.07
    1549 1168.75    1639 1169.58  1698.9 1167.74  1738.9 1164.18  1878.8  1140.9
#Mann= 3 , 0 , 0
       0     .08       0   549.2    .045       0   611.5     .08       0
Bank Sta=549.2,611.5
XS Rating Curve= 0 ,0
Exp/Cntr=0.3,0.1

Type RM Length L Ch R = 1 ,22963.2 ,394.8,394.1,393.3
XS GIS Cut Line= 2
     1833368.011      377871.527     1834372.245      378300.455
#Sta/Elev= 30
       0 1084.89   109.2 1063.84   178.7 1035.75   238.2 1015.53     268 1015.32
     278 1013.14   307.8 1000.44   317.7  997.81     407  1000.5   486.4   998.5
   515.2988.0115   536.1  985.11   555.9  986.18   566.9990.2043   595.6 1000.16
   665.1 1003.43   734.6  1003.1   754.5 1005.91   784.2 1015.33     814  1015.9
     824 1020.24   843.8 1032.46   873.6 1044.01   913.3 1051.18   933.2  1062.3
     953 1069.32  1012.6 1083.44  1042.4 1088.66  1072.2 1103.12    1092 1108.48
#Mann= 3 , 0 , 0
       0     .08       0   515.2    .045       0   566.9     .06       0
Bank Sta=515.2,566.9
XS Rating Curve= 0 ,0
Exp/Cntr=0.3,0.1

Type RM Length L Ch R = 1 ,22569.1 ,705.7,714.8,723.9
XS GIS Cut Line= 2
     1833394.882      378322.471     1834115.283      378598.361
#Sta/Elev= 30
       0 1047.68    49.4 1027.67      89 1015.01    98.9 1010.47   108.8 1007.23
   148.4  1005.1   187.9 1004.47   207.7  1006.1   227.5 1010.55   247.2 1010.54
   257.1 1008.45   276.9 1001.22   296.7  998.31   306.6  995.57   329.2 984.736
   336.3   982.4   344.4  982.39     356   982.7   365.9  984.21   405.5  984.26
   415.4  985.18     445  993.89   454.9  994.28   553.8  995.01     633  994.45
   642.8  996.56   652.7 1000.11   672.5 1001.36   702.2 1007.89   771.4 1019.03
#Mann= 3 , 0 , 0
       0     .08       0   329.2    .045       0   365.9     .06       0
Bank Sta=329.2,365.9
XS Rating Curve= 0 ,0
Exp/Cntr=0.3,0.1

Type RM Length L Ch R = 1 ,21854.3 ,811.8,795.8,778.5
XS GIS Cut Line= 4
     1832813.417      378522.736     1833299.999      378987.609
     1833424.713      379014.021     1834013.255      378685.896
#Sta/Elev= 30
       0 1144.46    19.8 1138.51    49.5 1123.64      99 1104.51   118.8  1099.7
   197.9 1067.78   217.7 1062.65   267.2 1044.59   296.9 1040.64   336.5  1046.2
   366.2  1046.4   425.6 1026.38   445.3 1022.49   494.8  998.96   524.5  993.49
   556.4  981.17     574  979.94     596982.2789   623.5  989.71   731.8  992.87
   889.6   991.4  1107.6   993.6  1256.3  992.52  1295.9   989.6  1365.3  991.61
  1385.1  998.73  1414.8 1003.92  1454.4 1003.28  1464.4  999.74  1474.3  999.32
#Mann= 3 , 0 , 0
       0     .08       0   556.4    .045       0     596     .06       0
Bank Sta=556.4,596
XS Rating Curve= 0 ,0
Exp/Cntr=0.3,0.1

Type RM Length L Ch R = 1 ,21058.5 ,380,389.2,399
XS GIS Cut Line= 2
     1832509.757      379554.042      1833806.63      379590.125
#Sta/Elev= 30
       0 1127.61      20  1123.9    39.9 1122.84    89.8 1110.61   149.7 1088.34
   219.6 1067.74   249.5 1056.23   309.4 1041.68   349.3 1027.27   409.2  986.16
   419.2  981.45   431.6977.9874   449.1  977.73   467.9979.5978     479  981.61
   618.8  981.77   688.6  983.91   718.6  986.99   748.5  995.48   758.5  995.58
   828.3 1017.23   878.2 1039.79   938.1 1058.85   948.1 1061.76    1008 1071.73
  1087.8 1094.75  1097.8  1098.1  1177.6 1134.43  1217.5 1145.52  1297.4 1158.25
#Mann= 3 , 0 , 0
       0      .1       0   431.6    .045       0   467.9     .06       0
Bank Sta=431.6,467.9
XS Rating Curve= 0 ,0
Exp/Cntr=0.3,0.1

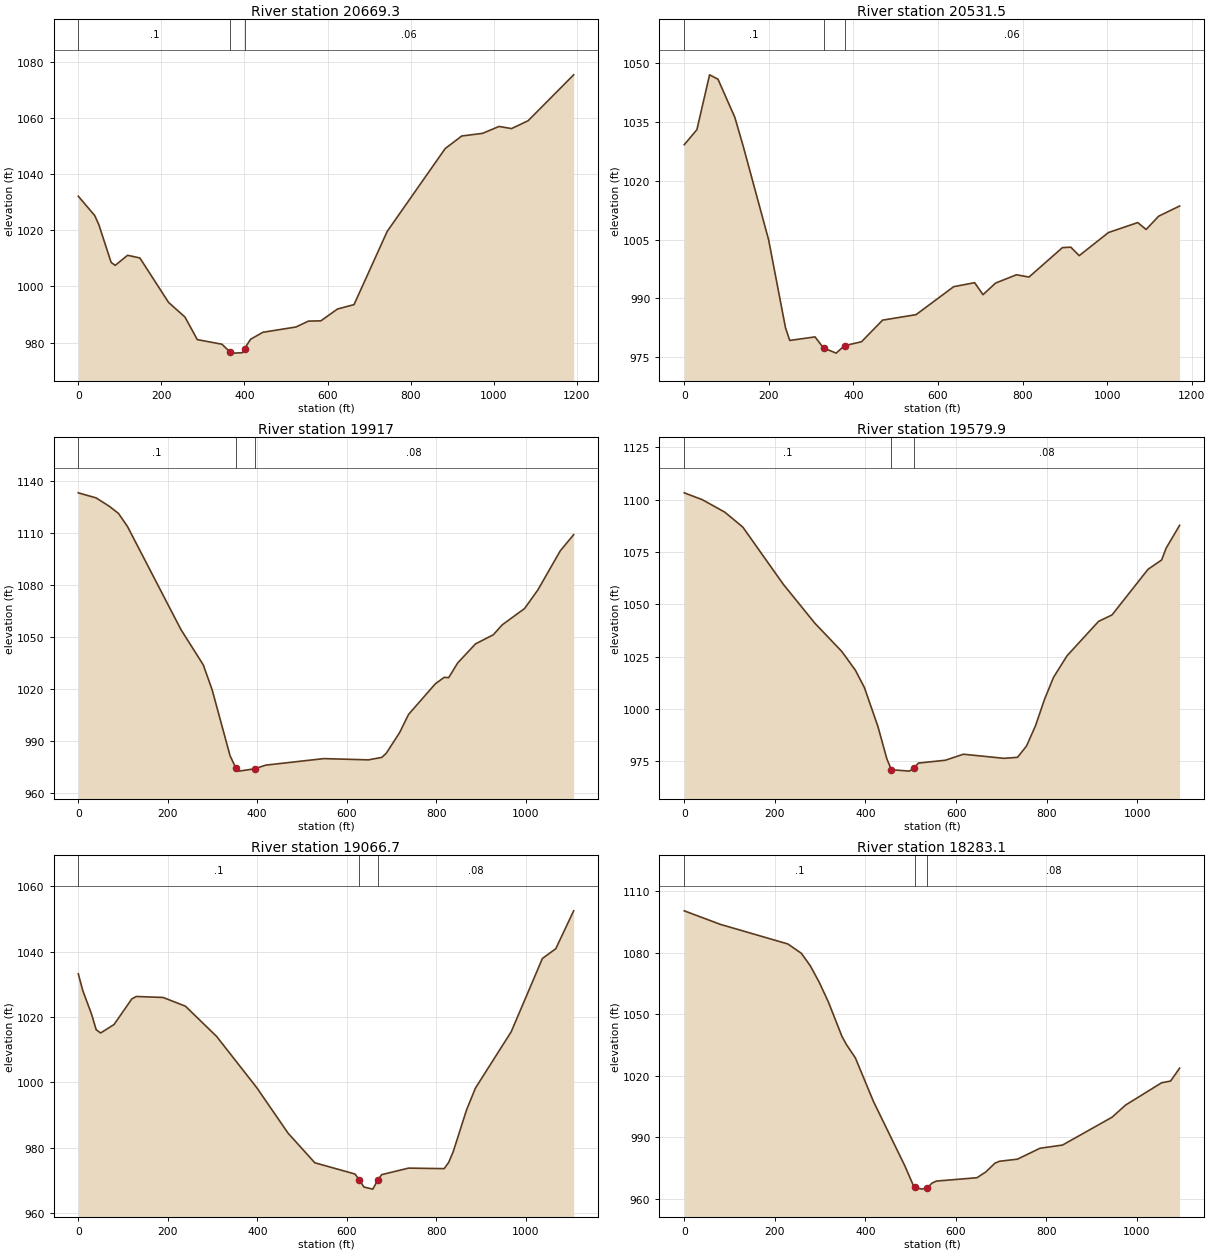
Type RM Length L Ch R = 1 ,20669.3 ,136.4,137.8,139.2
XS GIS Cut Line= 3
      1832682.32      379777.714     1833098.659      379983.284
     1833817.859       380098.73
#Sta/Elev= 30
       0 1032.08    39.5 1025.22    49.4 1021.98      79 1008.55    88.9 1007.48
   118.6 1011.07   148.2 1010.12   217.3  994.31   256.9  989.08   286.5  981.07
   345.8  979.43   366.1  976.57   375.4  976.26   395.2  976.42   400.2977.8384
   414.9  981.21   444.6  983.68   524.2  985.56   554.1  987.65   584.1  987.75
     624  991.95   663.9  993.52   743.7 1019.55   883.4 1049.04   923.3 1053.51
   973.2 1054.44  1013.1 1056.91  1043.1 1056.14    1083 1058.93  1192.7 1075.27
#Mann= 3 , 0 , 0
       0      .1       0   366.1    .045       0   400.2     .06       0
Bank Sta=366.1,400.2
XS Rating Curve= 0 ,0
Exp/Cntr=0.3,0.1

Type RM Length L Ch R = 1 ,20531.5 ,623.1,614.5,605.1
XS GIS Cut Line= 3
      1832635.39      379881.759     1833051.081      380119.698
     1833734.526      380230.674
#Sta/Elev= 30
       0 1029.24    29.9 1033.07    59.9 1047.07    79.8 1045.95   119.7  1036.2
   139.7 1028.75   199.6 1004.93   239.5  982.48   249.5  979.28   309.3  980.18
   329.3  977.36   359.2  976.04   379.2  977.95   419.1  978.94     469  984.46
   548.2  985.86   637.2     993   686.7  994.02   706.5  990.96   736.2  993.92
   785.6  996.04   815.3  995.46   894.4 1002.98   914.2 1003.08     934 1000.92
  1003.2 1006.82  1072.4 1009.36  1092.2  1007.6  1121.9 1010.99  1171.4 1013.59
#Mann= 3 , 0 , 0
       0      .1       0   329.3    .045       0   379.2     .06       0
Bank Sta=329.3,379.2
XS Rating Curve= 0 ,0
Exp/Cntr=0.3,0.1

Type RM Length L Ch R = 1 ,19917   ,338,337.2,336.4
XS GIS Cut Line= 2
     1832316.412      380431.219     1833410.992      380600.666
#Sta/Elev= 30
       0 1133.01    39.9 1130.08    69.8 1125.17    89.8 1121.15   109.8 1113.67
   229.5 1054.16   279.4 1033.81   299.4 1019.32   339.3  981.42   352.7 974.047
   359.2  972.52     394973.8536   419.1  975.97   548.8  979.74   648.6  979.02
   678.5  980.43   688.5   982.8   718.5  994.77   738.4 1005.22   798.3 1022.88
   818.2 1026.62   828.2 1026.44   848.2 1034.89   888.1 1045.89     928 1051.17
     948 1056.91   997.8 1066.27  1027.8 1077.11  1077.7 1099.58  1107.6 1108.88
#Mann= 3 , 0 , 0
       0      .1       0   352.7    .045       0     394     .08       0
Bank Sta=352.7,394
XS Rating Curve= 0 ,0
Exp/Cntr=0.3,0.1

Type RM Length L Ch R = 1 ,19579.9 ,514.2,513.1,512.1
XS GIS Cut Line= 2
     1832211.917       380768.14     1833297.526      380898.626
#Sta/Elev= 30
       0 1103.23    39.8 1099.96    89.5    1094   129.2 1086.88   218.7 1059.54
   288.3 1040.96   347.9 1027.44   377.7 1018.54   397.6 1010.27   427.4  991.71
   447.3  976.13   457.2     971     497  970.32     507  971.77   516.9  974.16
   576.5  975.53   616.3   978.4   705.8  976.43   735.6  976.91   755.5  982.31
   775.3  991.98   795.2 1004.58   815.1 1015.11   844.9  1025.4   914.5 1041.83
   944.3 1044.93  1023.8 1066.73  1053.7 1071.14  1063.6 1076.78  1093.4 1087.71
#Mann= 3 , 0 , 0
       0      .1       0   457.2    .045       0     507     .08       0
Bank Sta=457.2,507
XS Rating Curve= 0 ,0
Exp/Cntr=0.3,0.1

Type RM Length L Ch R = 1 ,19066.7 ,796.8,783.7,769.5
XS GIS Cut Line= 2
     1832088.014      381279.152     1833191.562       381362.23
#Sta/Elev= 30
       0 1033.18      10 1028.09    29.9 1020.75    39.9 1016.13    49.8 1015.12
    79.8  1017.7   119.6 1025.54   129.6 1026.27   189.4 1025.97   239.3 1023.31
   309.1 1014.06   398.8   998.4   468.6  984.53   528.4  975.48   618.1  972.05
   628.1  970.24   638.1  968.07     658  967.43   669.2970.2408     678  971.86
   737.8  973.85   817.5  973.69   827.5   975.6   837.5  978.82   867.4  991.62
   887.3   998.3   967.1 1015.47  1036.9 1037.88  1066.8 1040.86  1106.7 1052.43
#Mann= 3 , 0 , 0
       0      .1       0   628.1    .045       0   669.2     .08       0
Bank Sta=628.1,669.2
XS Rating Curve= 0 ,0
Exp/Cntr=0.3,0.1

Type RM Length L Ch R = 1 ,18283.1 ,360,366.6,373
XS GIS Cut Line= 2
     1832249.828       382316.83     1833192.899      381761.134
#Sta/Elev= 30
       0 1100.32    79.6 1093.74   228.9 1084.17   258.7 1079.64   278.6 1073.51
   298.5  1065.4   318.4 1055.96   348.3 1039.22   358.2  1035.2   378.1 1028.67
   417.9  1007.5   487.6  975.96   507.5  965.84   510.1965.5415   525.2  964.68
   537.5965.3629   547.3   967.6   557.3   968.6   646.8  970.24   666.7  973.11
   686.6  977.34   696.6  978.26   736.4  979.29   786.1   984.6   835.9  986.16
   945.4  999.74   975.2 1005.65  1054.8 1016.51  1074.7 1017.36  1094.6 1023.63
#Mann= 3 , 0 , 0
       0      .1       0   510.1    .045       0   537.5     .08       0
Bank Sta=510.1,537.5
XS Rating Curve= 0 ,0
Exp/Cntr=0.3,0.1

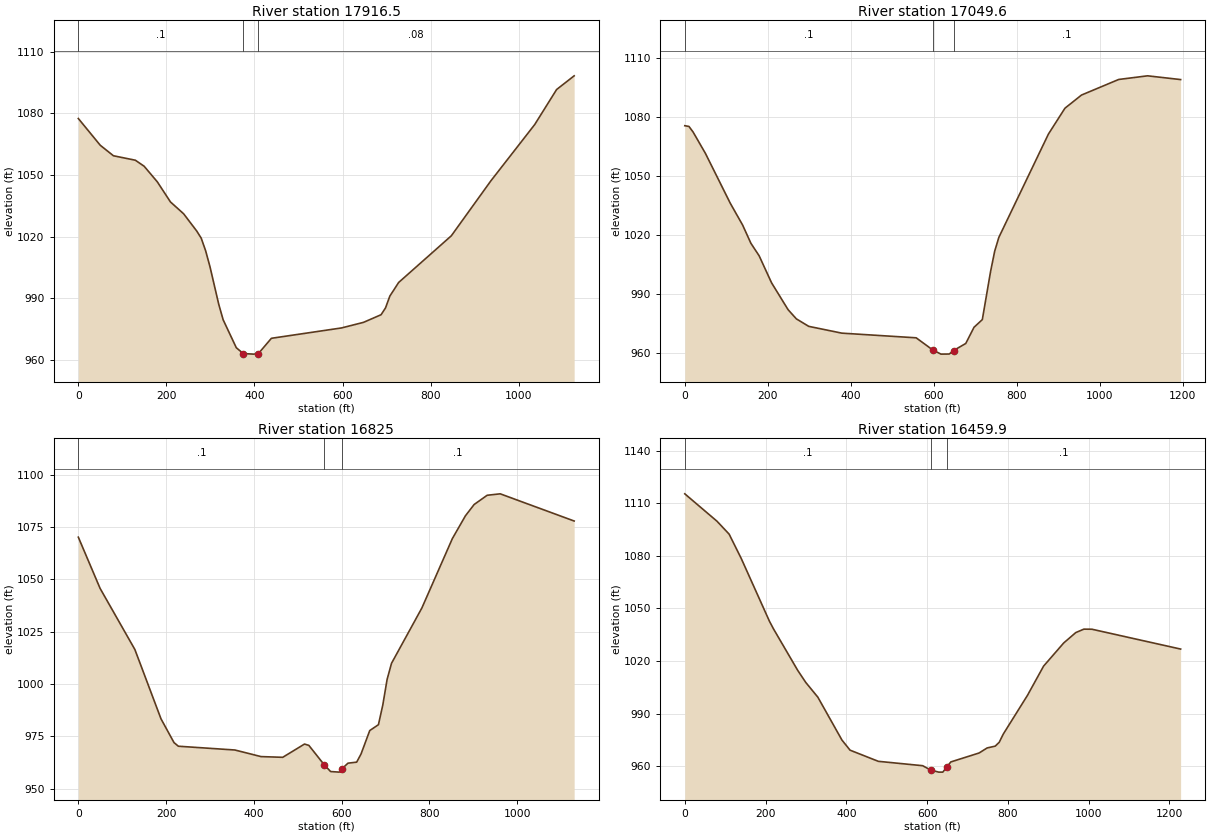
Type RM Length L Ch R = 1 ,17916.5 ,839.4,866.9,892.9
XS GIS Cut Line= 2
     1832523.556       382454.42     1833615.742      382180.787
#Sta/Elev= 30
       0 1077.42    49.8  1064.4    79.7 1059.29   129.5 1057.12   149.5 1054.18
   179.4 1046.59   209.2 1036.82   239.1 1031.06     269 1022.62     279 1019.21
     289 1013.12   298.9 1005.34   318.8  987.05   328.8   979.5   358.7  965.88
   374.6963.0218   398.6  962.76   408.8963.0113   438.4  970.46   597.8  975.51
   647.7  978.23   687.5  981.94   697.5  985.23   707.4  991.01   727.4  997.63
     847 1020.35   936.6 1047.03  1036.3 1074.47  1086.1 1091.53  1125.9 1098.19
#Mann= 3 , 0 , 0
       0      .1       0   374.6    .045       0   408.8     .08       0
Bank Sta=374.6,408.8
XS Rating Curve= 0 ,0
Exp/Cntr=0.3,0.1

Type RM Length L Ch R = 1 ,17049.6 ,227.7,224.6,222.7
XS GIS Cut Line= 2
     1832451.425      382515.048     1833149.878      383484.602
#Sta/Elev= 30
       0 1075.47      10 1075.11    19.9 1072.31    49.8 1061.41   109.5  1036.2
   139.4 1025.09   159.3 1015.86   179.2 1009.51   209.1  995.82   248.9   982.2
   268.9  977.53   298.7  973.74   378.4   970.3   557.6  967.93   597.5  961.78
   617.4  959.66   637.3  959.71   647.8961.4926   677.1  965.06     697  973.27
     717  977.16   736.9 1001.54   746.8 1011.84   756.8 1018.84   876.3 1071.23
   916.1 1084.34     956 1091.02  1045.6 1098.92  1115.3 1100.77  1194.9 1098.87
#Mann= 3 , 0 , 0
       0      .1       0   597.5    .045       0   647.8      .1       0
Bank Sta=597.5,647.8
XS Rating Curve= 0 ,0
Exp/Cntr=0.3,0.1

Type RM Length L Ch R = 1 ,16825   ,372.7,365.1,361.5
XS GIS Cut Line= 2
     1832247.214      382730.669       1833021.5      383553.848
#Sta/Elev= 30
       0 1070.14    49.6 1045.67   128.9 1016.46   188.4  983.35   218.1  971.98
     228  970.26   356.9  968.45   416.4   965.3   465.9  964.96   515.5  971.29
   525.4  970.66   560.9961.2761     575  958.16   594.8  957.88   600.8959.4497
   614.6  962.16   634.4  962.65   644.4  966.56   664.2  977.74     684  980.54
   693.9   989.9   703.8  1002.2   713.8 1009.86   783.1 1036.34   852.5 1069.46
   882.3 1080.35   902.1 1085.74   931.8 1090.16   961.6 1090.85  1130.1 1077.86
#Mann= 3 , 0 , 0
       0      .1       0   560.9    .045       0   600.8      .1       0
Bank Sta=560.9,600.8
XS Rating Curve= 0 ,0
Exp/Cntr=0.3,0.1

Type RM Length L Ch R = 1 ,16459.9 ,648.3,639.7,627.1
XS GIS Cut Line= 2
     1831874.865      382939.337       1832809.3      383735.504
#Sta/Elev= 30
       0 1115.32    79.8 1099.69   109.8 1092.34   139.7 1078.51   209.6 1042.72
   219.6 1038.37   279.5 1014.76   299.4 1007.89   329.4  999.46   389.2  974.98
   409.2  969.26   479.1  962.91   588.9  960.41   608.8  957.92   628.8  956.75
   638.8  956.75   648.7   959.7   658.7  962.56   728.6  967.65   748.6  970.53
   768.5  971.55   778.5  973.76   788.5  978.42   848.4 1000.49   888.3 1017.14
   938.2 1030.36   968.1 1036.27   988.1 1038.22    1008 1038.17  1227.6 1026.87
#Mann= 3 , 0 , 0
       0      .1       0   608.8    .045       0   648.7      .1       0
Bank Sta=608.8,648.7
XS Rating Curve= 0 ,0
Exp/Cntr=0.3,0.1