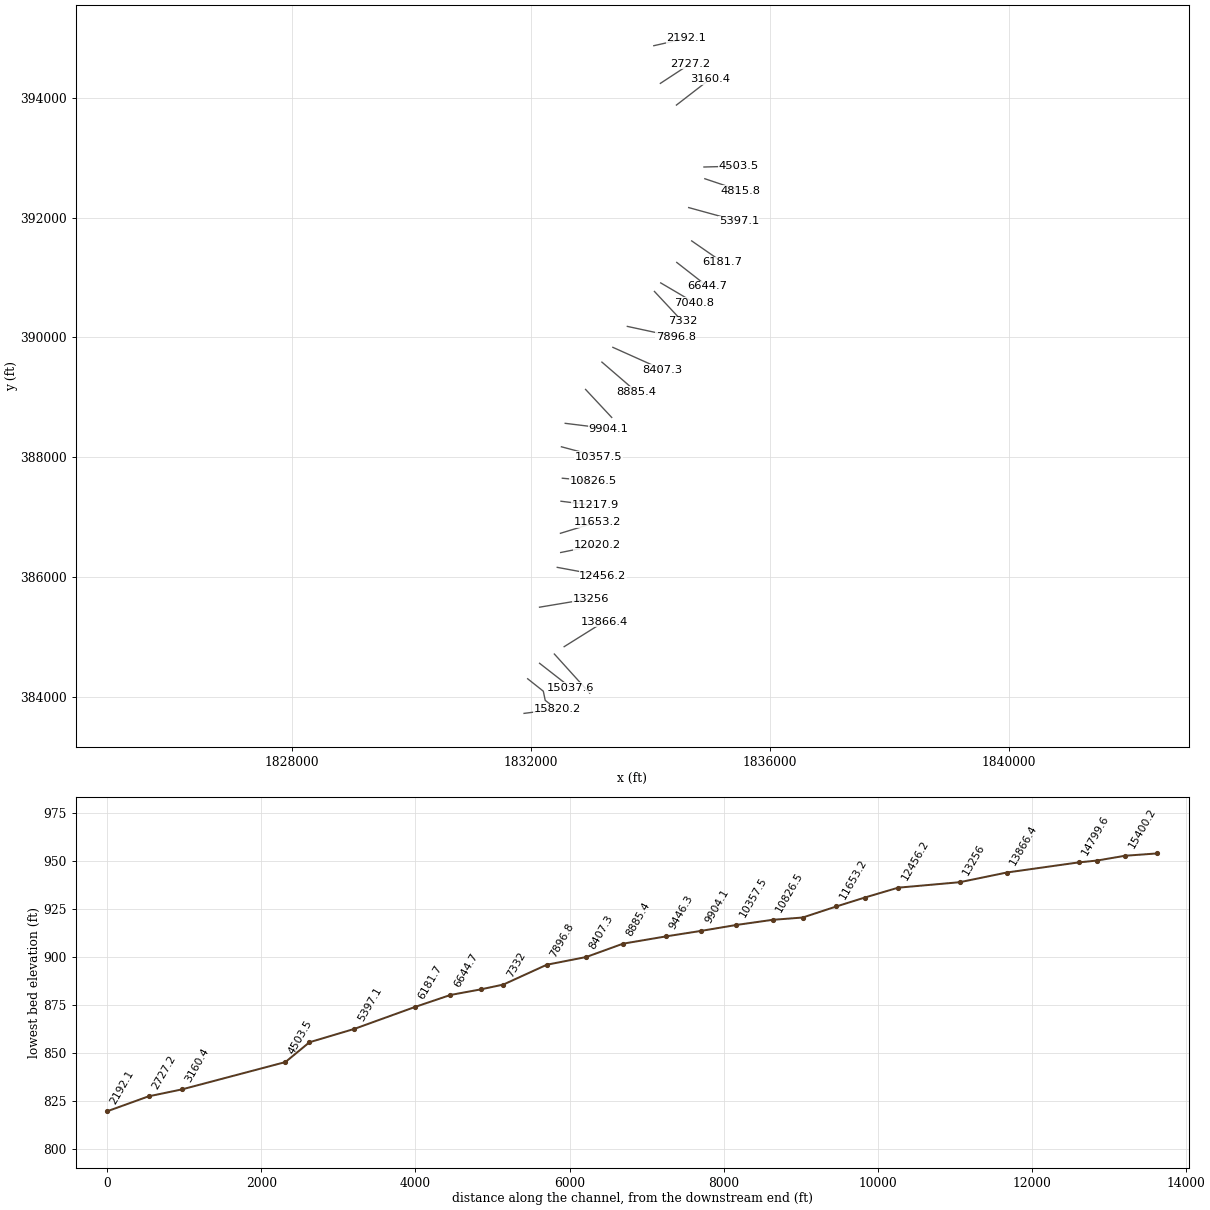
HEC-RAS study BoothsCk.prj: BoothsCk

--- BoothsCk.g01 (geometry) --- (continued)

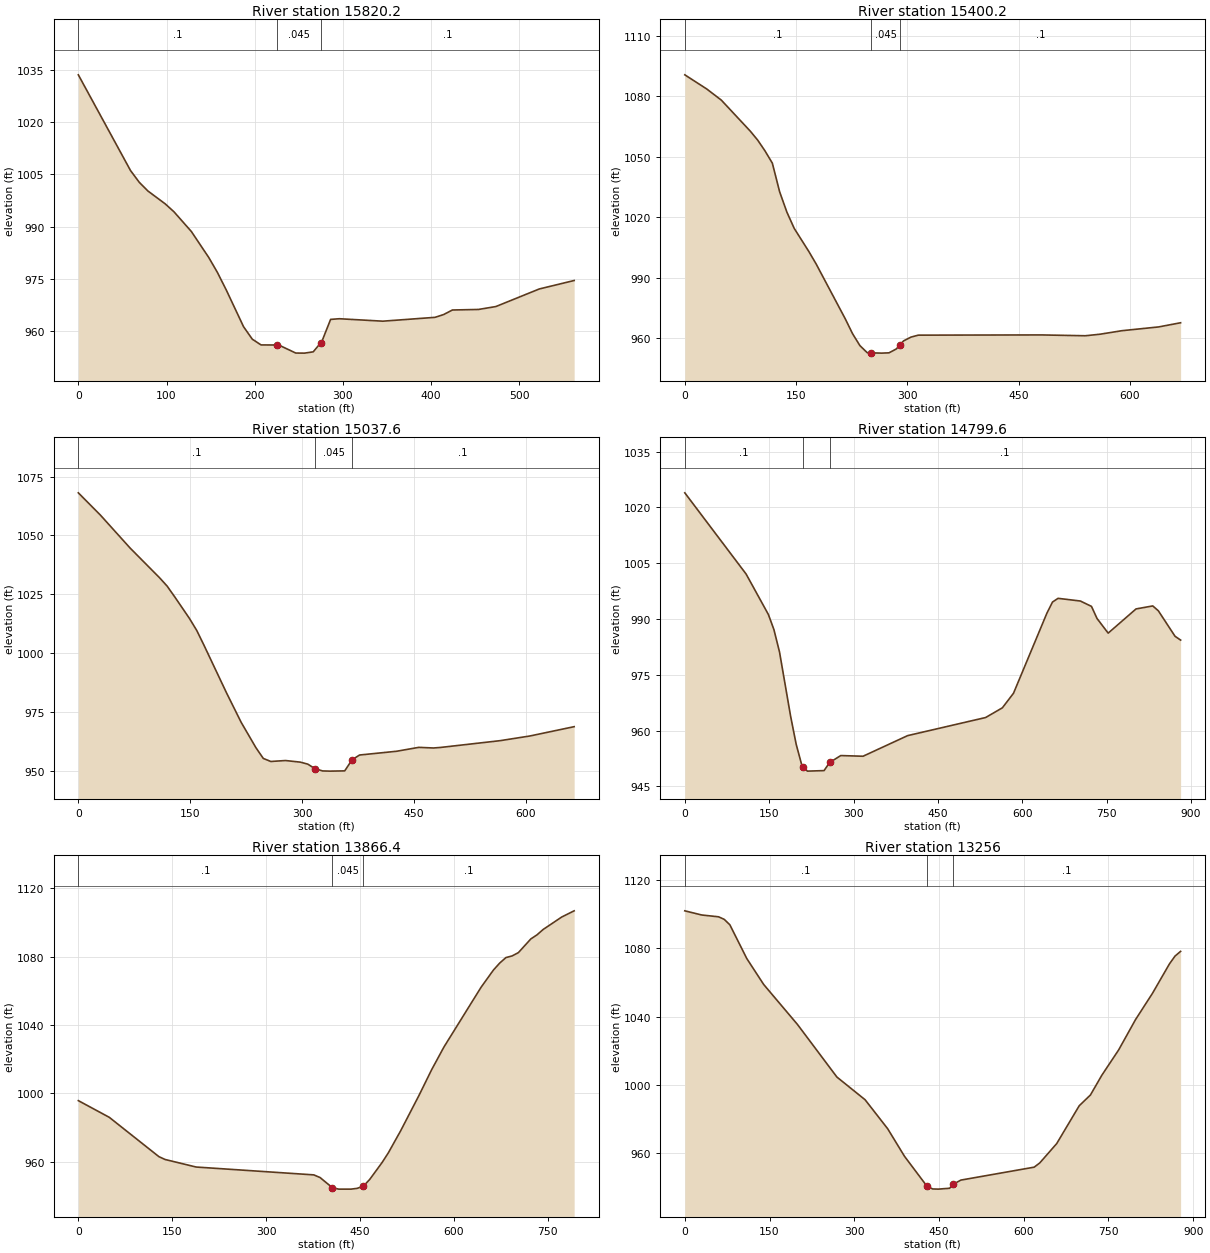
Type RM Length L Ch R = 1 ,15820.2 ,438.5,420,401.5
XS GIS Cut Line= 2
     1831884.896      383730.488     1832442.682      383801.704
#Sta/Elev= 30
       0  1033.5    59.2 1006.08    69.1 1002.72    78.9 1000.23    98.6  996.53
   108.5  994.26   128.2  988.62     148  981.15   157.8  976.87   167.7  971.91
   187.4  961.35   197.3  957.78   207.2  956.14     225956.1158   226.9  956.16
   246.6  953.81   256.5  953.79   266.4  954.16   274.8956.7143   276.2  957.14
   286.1  963.45     296  963.64   345.3  962.94   404.5  964.04   414.3  964.84
   424.2  966.14   453.8   966.3   473.5  967.13   522.8  972.17   562.3  974.59
#Mann= 3 , 0 , 0
       0      .1       0     225    .045       0   274.8      .1       0
Bank Sta=225,274.8
XS Rating Curve= 0 ,0
Exp/Cntr=0.3,0.1

Type RM Length L Ch R = 1 ,15400.2 ,363,362.7,362.9
XS GIS Cut Line= 4
     1831944.792      384307.745     1832206.999      384100.433
     1832238.906      383947.534     1832379.925      383839.181
#Sta/Elev= 30
       0 1090.67    29.5 1083.67    49.2 1078.13    88.5 1062.63    98.3 1058.24
   108.1 1052.92     118 1046.84   127.8 1032.66   137.6 1022.54   147.5 1014.45
   167.1 1003.05     177  996.83   216.3  969.57   226.1  962.22     236   956.3
   245.8   952.8   250.7952.7039   265.4  952.56   275.3  952.71   285.1  954.63
   290.5956.8396   294.9  958.64   304.8   960.5   314.6  961.48   480.7  961.59
   539.8  961.18   559.6  961.94   589.2  963.69   638.6  965.56   668.3  967.63
#Mann= 3 , 0 , 0
       0      .1       0   250.7    .045       0   290.5      .1       0
Bank Sta=250.7,290.5
XS Rating Curve= 0 ,0
Exp/Cntr=0.3,0.1

Type RM Length L Ch R = 1 ,15037.6 ,241.3,238,233.8
XS GIS Cut Line= 2
     1832144.444      384565.558     1832669.618      384157.571
#Sta/Elev= 30
       0 1068.08    29.8 1058.57    69.5 1044.65   109.2 1031.99   119.1 1028.53
     129  1024.1   148.9 1014.89   158.8 1009.74   168.7 1003.35   198.5  983.43
   218.4  970.77   238.2  960.01   248.1  955.46   258.1  954.17   277.9  954.57
   297.8  953.89   307.7  953.05   317.6  951.09   327.6  950.16   337.5  950.08
   357.3  950.19   367.2  954.93   377.2  956.91   426.8   958.5   456.6  960.16
   476.4  959.89   486.4  960.14   565.8     963   605.5  964.97     665  968.93
#Mann= 3 , 0 , 0
       0      .1       0   317.6    .045       0   367.2      .1       0
Bank Sta=317.6,367.2
XS Rating Curve= 0 ,0
Exp/Cntr=0.3,0.1

Type RM Length L Ch R = 1 ,14799.6 ,898.5,933.2,966.6
XS GIS Cut Line= 2
      1832391.84      384720.071     1832984.286      384067.368
#Sta/Elev= 30
       0  1023.9     109 1002.08   148.6  991.21   158.5  987.13   168.4  981.13
   188.2  963.81   198.1  956.29     208  950.74   210.9950.2655   217.9  949.12
   247.6  949.26   257.5  951.44   277.3   953.3   316.9  953.12   396.2  958.66
   534.8  963.52   564.6  966.13   584.4  970.05   643.8  991.57   653.7  994.55
   663.6  995.55   703.2  994.83     723  993.39   732.9  990.13   752.7   986.2
   802.2   992.7     832  993.51   841.9   992.2   871.6  985.35   881.5  984.33
#Mann= 3 , 0 , 0
       0      .1       0   210.9    .045       0   257.5      .1       0
Bank Sta=210.9,257.5
XS Rating Curve= 0 ,0
Exp/Cntr=0.3,0.1

Type RM Length L Ch R = 1 ,13866.4 ,619.4,610.4,601.5
XS GIS Cut Line= 2
     1832556.028      384843.097      1833228.27      385262.387
#Sta/Elev= 30
       0  995.68    49.5  985.89   128.8  962.87   138.6  961.22   188.2   956.8
   376.3   952.2   386.2  950.66     406   944.7     416  943.86   435.8  943.86
   445.7  944.32   455.6  945.65   465.5  949.48   485.3   959.4   495.2     965
     515  977.97   544.7  998.99   564.5 1013.73   584.3 1027.12   643.7 1062.14
   663.5 1072.22   673.4 1076.24   683.3 1079.44   693.2 1080.41   703.2 1082.34
     723 1090.33   732.9 1092.74   742.8  1095.9   772.5  1103.2   792.3 1106.81
#Mann= 3 , 0 , 0
       0      .1       0     406    .045       0   455.6      .1       0
Bank Sta=406,455.6
XS Rating Curve= 0 ,0
Exp/Cntr=0.3,0.1

Type RM Length L Ch R = 1 ,13256   ,810.9,799.8,793
XS GIS Cut Line= 2
     1832143.596      385501.435     1833009.502      385645.654
#Sta/Elev= 30
       0  1102.1    29.9 1099.66    59.8 1098.59    69.8  1097.1    79.8  1093.9
   109.7 1074.13   139.7 1058.88   199.5 1035.43   269.3 1004.58   319.2  991.27
   359.1   974.3     389  958.07   428.9  940.47   438.9  938.93   448.9  938.83
   468.8  939.34   475.5 941.752   488.8  944.13   618.5  951.71   628.4  954.19
   658.4  965.54   698.3  987.74   718.2  994.09   738.2 1005.58   768.1  1020.5
     798  1038.3     828 1053.72   857.9  1070.9   867.9 1075.56   877.8 1078.32
#Mann= 3 , 0 , 0
       0      .1       0   428.9    .045       0   475.5      .1       0
Bank Sta=428.9,475.5
XS Rating Curve= 0 ,0
Exp/Cntr=0.3,0.1

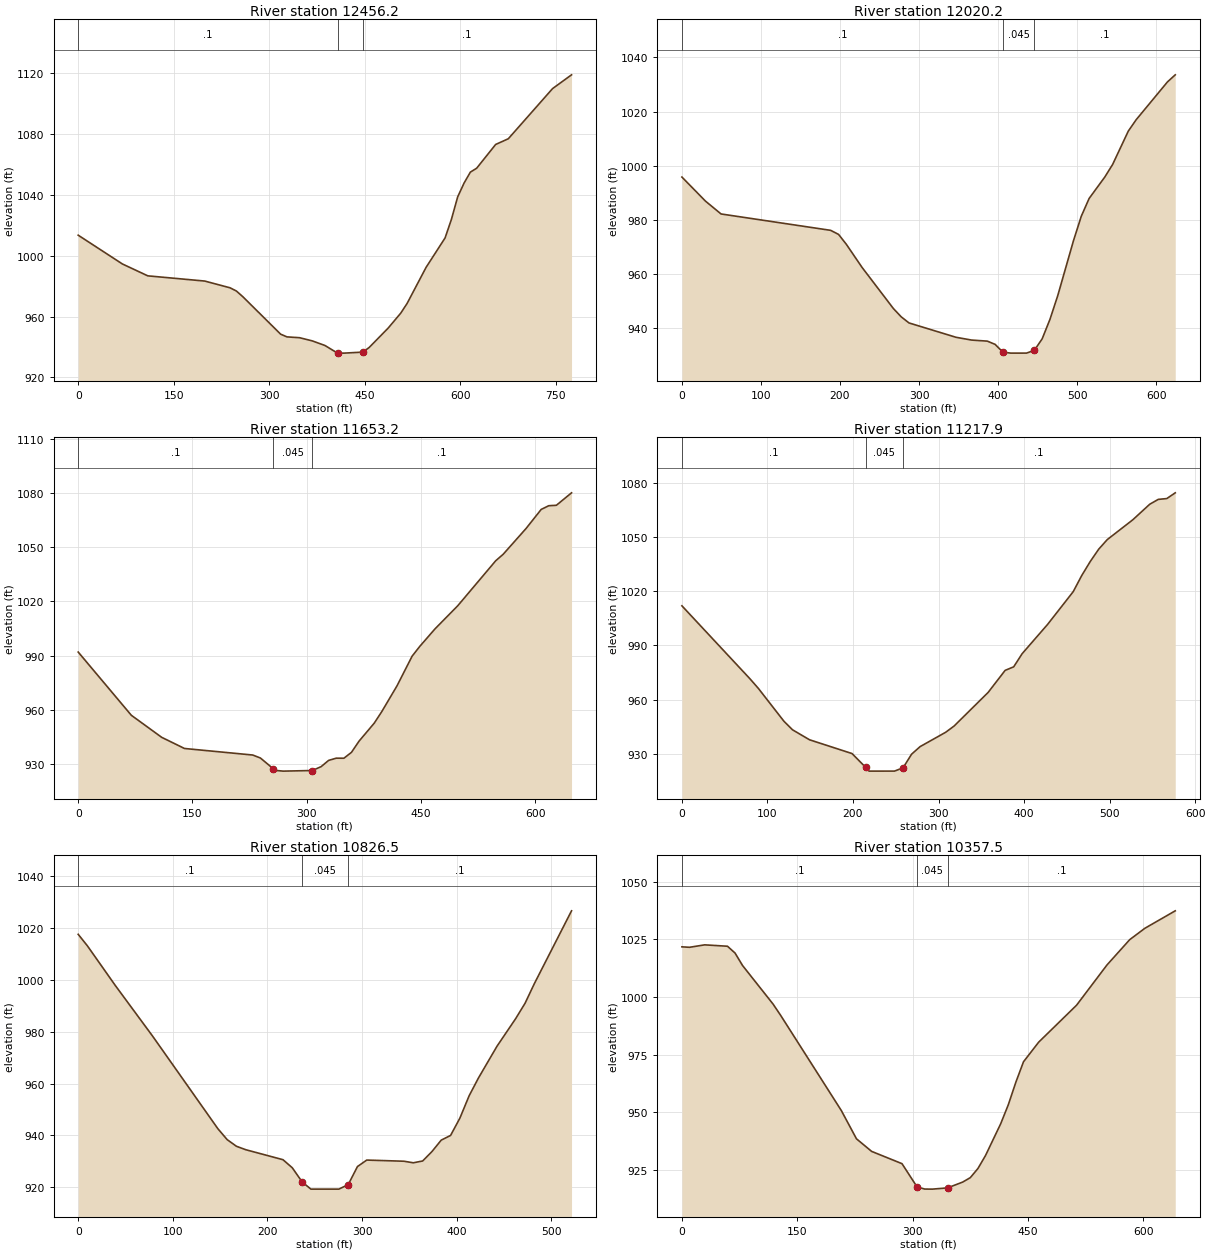
Type RM Length L Ch R = 1 ,12456.2 ,427,436,445.1
XS GIS Cut Line= 2
     1832440.292      386165.819     1833202.255      386025.126
#Sta/Elev= 30
       0 1013.35    69.5  994.45   109.3  986.68   198.7  983.26   238.4  978.85
   248.4  976.73   258.3   973.1   317.9  948.43   327.8  946.64   347.7  946.09
   367.6  944.01   387.4  941.02   407.3  935.99   417.2  935.98     447  936.64
     457   939.7   486.8   952.4   506.6  962.23   516.6   968.6   546.4  992.27
   576.2 1011.56   586.1 1023.67     596  1038.5     606 1047.54   615.9 1054.72
   625.8 1057.29   655.6 1072.86   675.5 1076.62     745 1109.52   774.8 1118.56
#Mann= 3 , 0 , 0
       0      .1       0   407.3    .045       0     447      .1       0
Bank Sta=407.3,447
XS Rating Curve= 0 ,0
Exp/Cntr=0.3,0.1

Type RM Length L Ch R = 1 ,12020.2 ,365,367,368.7
XS GIS Cut Line= 2
     1832497.888      386413.399     1833109.838      386536.484
#Sta/Elev= 30
       0  995.84    29.7  986.98    49.5  982.21   188.2  976.16   198.2  974.66
   208.1  970.98   227.9  962.48   267.5  947.31   277.4  944.24   287.3  941.97
   346.8  936.67   366.6  935.64   386.4  935.25   396.3  934.05   406.2  931.17
   416.1  930.82     436  930.83   445.9  931.84   455.8   936.1   465.7  943.31
   475.6  952.13   495.4  972.32   505.3  981.37   515.2  987.92     535  995.83
   544.9 1000.46   564.8 1012.81   574.7 1016.99   614.3 1030.96   624.2 1033.59
#Mann= 3 , 0 , 0
       0      .1       0   406.2    .045       0   445.9      .1       0
Bank Sta=406.2,445.9
XS Rating Curve= 0 ,0
Exp/Cntr=0.3,0.1

Type RM Length L Ch R = 1 ,11653.2 ,444.8,435.3,425.8
XS GIS Cut Line= 2
     1832493.635      386733.917     1833112.901      386923.056
#Sta/Elev= 30
       0  992.04    69.7   957.1   109.6  944.89   139.5  938.73   229.1  935.11
   239.1  933.47   255.7  927.64     259  926.61     269  926.21   307.2926.5396
   318.8  928.68   328.7  932.15   338.7  933.37   348.7  933.34   358.6  936.56
   368.6  942.78   388.5  952.71   398.5  959.15   418.4  973.34   438.3  989.78
   448.3  995.16   468.2 1004.81   498.1 1017.61   547.9 1042.47   557.8 1046.11
   587.7 1060.29   607.7  1070.9   617.6 1072.94   627.6 1073.18   647.5 1080.07
#Mann= 3 , 0 , 0
       0      .1       0   255.7    .045       0   307.2      .1       0
Bank Sta=255.7,307.2
XS Rating Curve= 0 ,0
Exp/Cntr=0.3,0.1

Type RM Length L Ch R = 1 ,11217.9 ,390.7,391.4,392
XS GIS Cut Line= 2
     1832502.797      387268.629     1833075.267      387197.809
#Sta/Elev= 30
       0 1011.86    79.6   971.5    89.5  966.14   119.3  948.04   129.3  943.33
   149.2  937.81   198.9  930.19   214.7  922.63   218.8  920.48   248.6   920.5
   258.6  922.32   268.5  929.84   278.5  934.03   308.3  941.94   318.2   945.4
     358  963.98   377.9  976.18   387.9  978.14   397.8  985.41   427.6 1001.62
   457.5 1019.69   467.4 1028.56   477.4 1036.35   487.3 1043.17   497.3 1048.47
   527.1  1059.4     547 1068.03   556.9  1070.7   566.9 1071.15   576.8 1074.33
#Mann= 3 , 0 , 0
       0      .1       0   214.7    .045       0   258.6      .1       0
Bank Sta=214.7,258.6
XS Rating Curve= 0 ,0
Exp/Cntr=0.3,0.1

Type RM Length L Ch R = 1 ,10826.5 ,472.8,469,465.1
XS GIS Cut Line= 2
     1832525.367      387652.568     1833044.415      387603.795
#Sta/Elev= 30
       0 1017.58     9.8 1013.09    39.4  997.74    78.7  978.26   147.6  942.58
   157.4  938.38   167.2  935.81   177.1  934.48   216.4  930.63   226.2  927.52
   236.7  922.03   245.9  919.28   275.4  919.28   285.3  921.01   295.1  927.99
   304.9  930.49   344.3  930.04   354.1  929.44     364  930.14   373.8  933.77
   383.6  938.18   393.5     940   403.3  946.65   413.1   955.3     423  962.19
   442.6  974.44   462.3  985.07   472.2  990.99     482  998.54   521.3 1026.64
#Mann= 3 , 0 , 0
       0      .1       0   236.7    .045       0   285.3      .1       0
Bank Sta=236.7,285.3
XS Rating Curve= 0 ,0
Exp/Cntr=0.3,0.1

Type RM Length L Ch R = 1 ,10357.5 ,450.1,453.4,456.5
XS GIS Cut Line= 2
     1832510.254      388176.597     1833130.041      388011.956
#Sta/Elev= 30
       0 1021.79     9.9 1021.59    29.6 1022.65    59.2 1022.05    69.1 1019.08
    78.9 1013.64   118.4  996.98   128.3  992.07   207.2  950.74   226.9  938.46
   246.6     933   286.1  927.67   305.7  917.56   315.7  916.65   325.6  916.62
   345.3  917.16     365  919.68   374.9  921.61   384.8  925.57   394.6  931.17
   414.4  945.01   424.2  953.17   434.1  963.04     444  971.88   463.7  980.39
     513  996.45   552.5  1013.9   582.1 1024.91   601.8 1029.84   641.3 1037.42
#Mann= 3 , 0 , 0
       0      .1       0   305.7    .045       0   345.3      .1       0
Bank Sta=305.7,345.3
XS Rating Curve= 0 ,0
Exp/Cntr=0.3,0.1

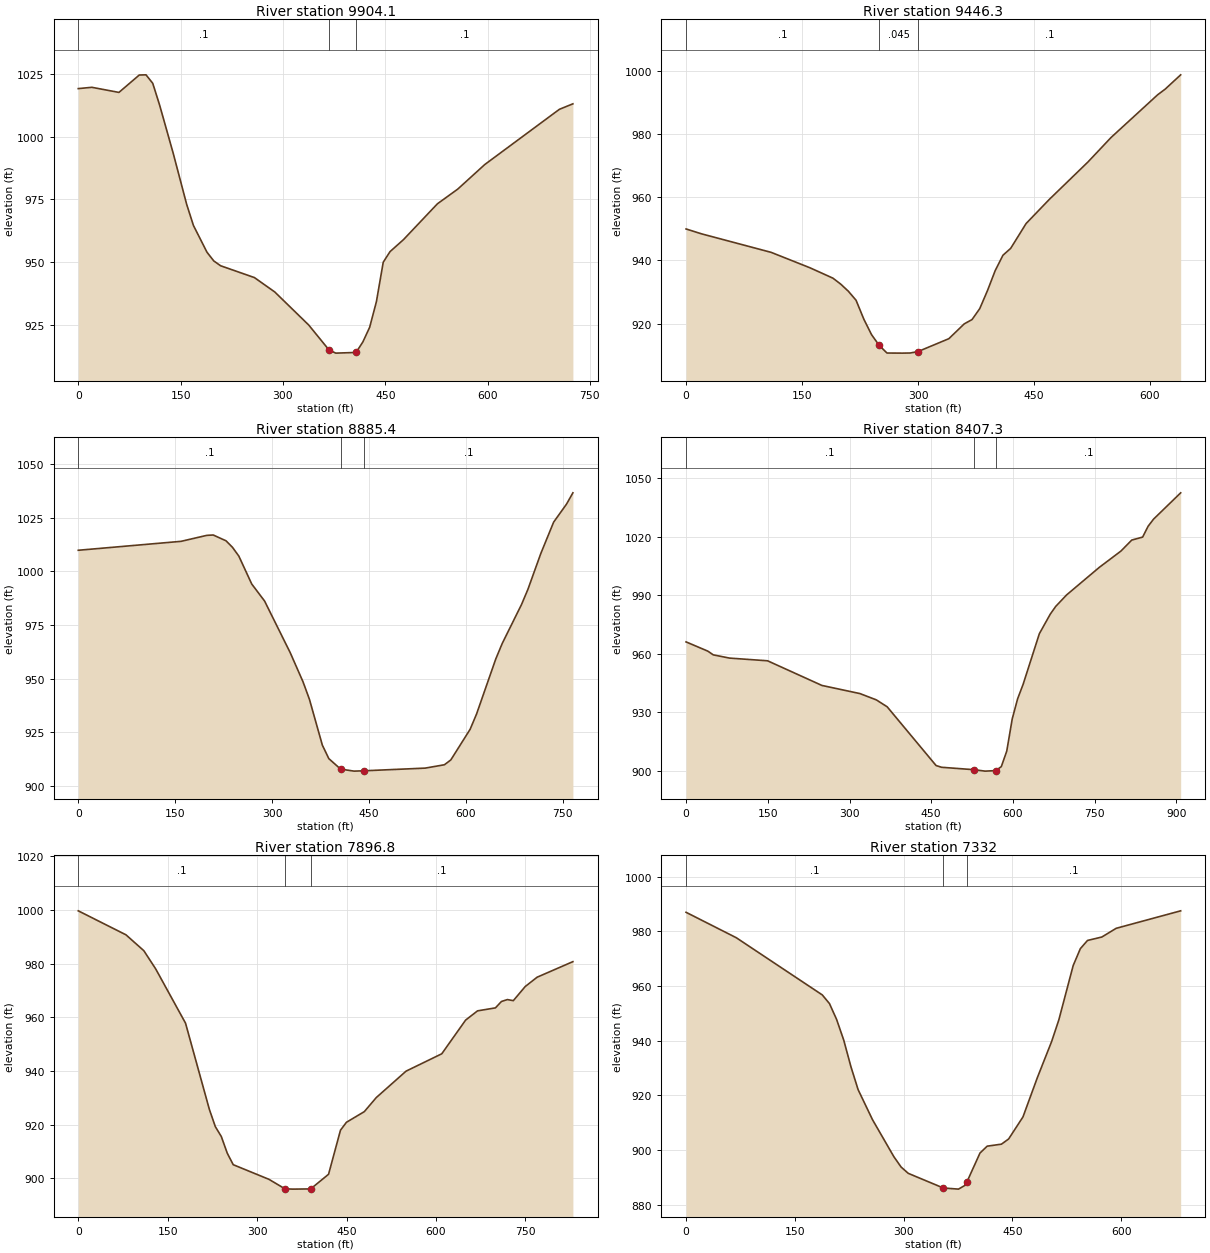
Type RM Length L Ch R = 1 ,9904.1  ,473.6,457.7,441.9
XS GIS Cut Line= 2
     1832573.672      388567.926     1833293.336      388479.681
#Sta/Elev= 30
       0 1019.31    19.9 1019.83    59.6 1017.79    89.4 1024.74    99.3 1024.82
   109.2 1021.41   119.2 1012.76     139  993.62   158.9  973.04   168.8  964.61
   188.7  953.89   198.6  950.43   208.6   948.5   258.2  943.77     288  938.02
   337.7  924.83   367.5  914.85   377.4  913.57   407.2  913.84   417.2  918.07
   427.1  923.89     437  934.14     447  949.91   456.9  954.12   476.8  958.97
   526.4  973.26   556.2  979.13   595.9  988.97   705.2 1011.03     725 1013.23
#Mann= 3 , 0 , 0
       0      .1       0   367.5    .045       0   407.2      .1       0
Bank Sta=367.5,407.2
XS Rating Curve= 0 ,0
Exp/Cntr=0.3,0.1

Type RM Length L Ch R = 1 ,9446.3  ,558.6,561,563.4
XS GIS Cut Line= 2
     1832914.035      389133.566     1833351.324      388666.538
#Sta/Elev= 30
       0  949.94      20   948.4     110  942.55     160   937.7   189.9   934.4
   199.9  932.54   209.9  930.27   219.9  927.41   229.9  921.46   239.9  916.55
   249.9  913.12   259.9  910.73   279.9   910.7   289.9  910.74   299.9  911.18
   339.9  915.26   359.9  919.96   369.9   921.3   379.9  924.77   389.9  930.47
   399.9  936.79   409.9  941.63   419.9  943.81   439.9  951.67   469.8  959.26
   519.8  971.09   549.8  978.86   609.8   992.3   619.8  994.14   639.8  998.65
#Mann= 3 , 0 , 0
       0      .1       0   249.9    .045       0   299.9      .1       0
Bank Sta=249.9,299.9
XS Rating Curve= 0 ,0
Exp/Cntr=0.3,0.1

Type RM Length L Ch R = 1 ,8885.4  ,470.7,478.1,485.4
XS GIS Cut Line= 2
      1833187.53      389589.153     1833768.083       389090.36
#Sta/Elev= 30
       0 1009.81     159 1013.97   198.8 1016.75   208.8 1016.93   228.6 1014.23
   238.6  1011.2   248.5 1007.08   268.4   994.1   288.3  986.16     328  962.08
   347.9  948.43   357.8  940.27   377.7  919.01   387.7  912.72     406907.8212
   426.8  906.89   441.9907.0431   536.8  908.29   566.6  909.86   576.5  912.11
   606.4   926.4   616.3  933.48   646.1  959.19   656.1  966.41   685.9  984.53
   695.8   991.6   715.7 1008.26   735.6 1022.92   755.5  1031.3   765.4 1036.58
#Mann= 3 , 0 , 0
       0      .1       0     406    .045       0   441.9      .1       0
Bank Sta=406,441.9
XS Rating Curve= 0 ,0
Exp/Cntr=0.3,0.1

Type RM Length L Ch R = 1 ,8407.3  ,506.5,510.5,514.3
XS GIS Cut Line= 2
     1833370.946       389835.36     1834199.795      389465.054
#Sta/Elev= 30
       0  966.14    39.9  961.41    49.9   959.5    79.8  957.84   149.6  956.46
   249.4  943.83   319.2  939.66   349.2  936.44   369.1   932.9   458.9   902.8
   468.9  901.92   528.7  900.68   548.7  899.95   568.6  900.22   578.6  902.27
   588.6  910.21   598.6  926.67   608.5  936.98   618.5  944.31   648.4  970.33
   668.4  980.33   678.4  984.29   698.3  990.17   758.2 1004.26   798.1 1012.65
     818 1018.29     838 1019.83     848 1025.36   857.9 1028.98   907.8 1042.49
#Mann= 3 , 0 , 0
       0      .1       0   528.7    .045       0   568.6      .1       0
Bank Sta=528.7,568.6
XS Rating Curve= 0 ,0
Exp/Cntr=0.3,0.1

Type RM Length L Ch R = 1 ,7896.8  ,577.7,564.8,551.9
XS GIS Cut Line= 2
     1833613.323       390184.55     1834424.492      390010.571
#Sta/Elev= 30
       0  999.63      80  990.69     110  984.77   129.9  977.98   179.9  957.78
   219.9  925.64   229.9  919.23   239.9  915.56   249.9  909.35   259.9  905.06
   319.8  899.61   346.7  896.07   359.8  895.96   389.8  896.04   419.8   901.5
   439.8  917.92   449.8  920.86   479.8  924.83   499.8  930.06   549.8  939.91
   609.7  946.38   649.7  958.93   669.7  962.37   699.7  963.48   709.7  965.85
   719.7  966.57   729.7  966.17   749.6  971.42   769.6   974.9   829.6   980.7
#Mann= 3 , 0 , 0
       0      .1       0   346.7    .045       0   389.8      .1       0
Bank Sta=346.7,389.8
XS Rating Curve= 0 ,0
Exp/Cntr=0.3,0.1

Type RM Length L Ch R = 1 ,7332    ,284.8,291.2,297.8
XS GIS Cut Line= 2
     1834066.585      390767.488     1834532.871       390269.49
#Sta/Elev= 30
       0  986.92    69.2  977.63   187.9  956.69   197.8  953.52   207.6  947.75
   217.5  940.13   227.4  930.42   237.3  922.04   257.1  911.07   286.7  897.47
   296.6  893.72   306.5  891.41   354.7886.0664   375.7  885.64   385.6  887.15
   387.1888.1167   405.4  898.84   415.3  901.36     435  902.09   444.9  903.99
   464.7  912.07   484.5  926.42   504.2  939.64   514.1  947.52   533.9  967.41
   543.8  973.61   553.7  976.62   573.5  977.88   593.2  981.06   682.2  987.46
#Mann= 3 , 0 , 0
       0      .1       0   354.7    .045       0   387.1      .1       0
Bank Sta=354.7,387.1
XS Rating Curve= 0 ,0
Exp/Cntr=0.3,0.1

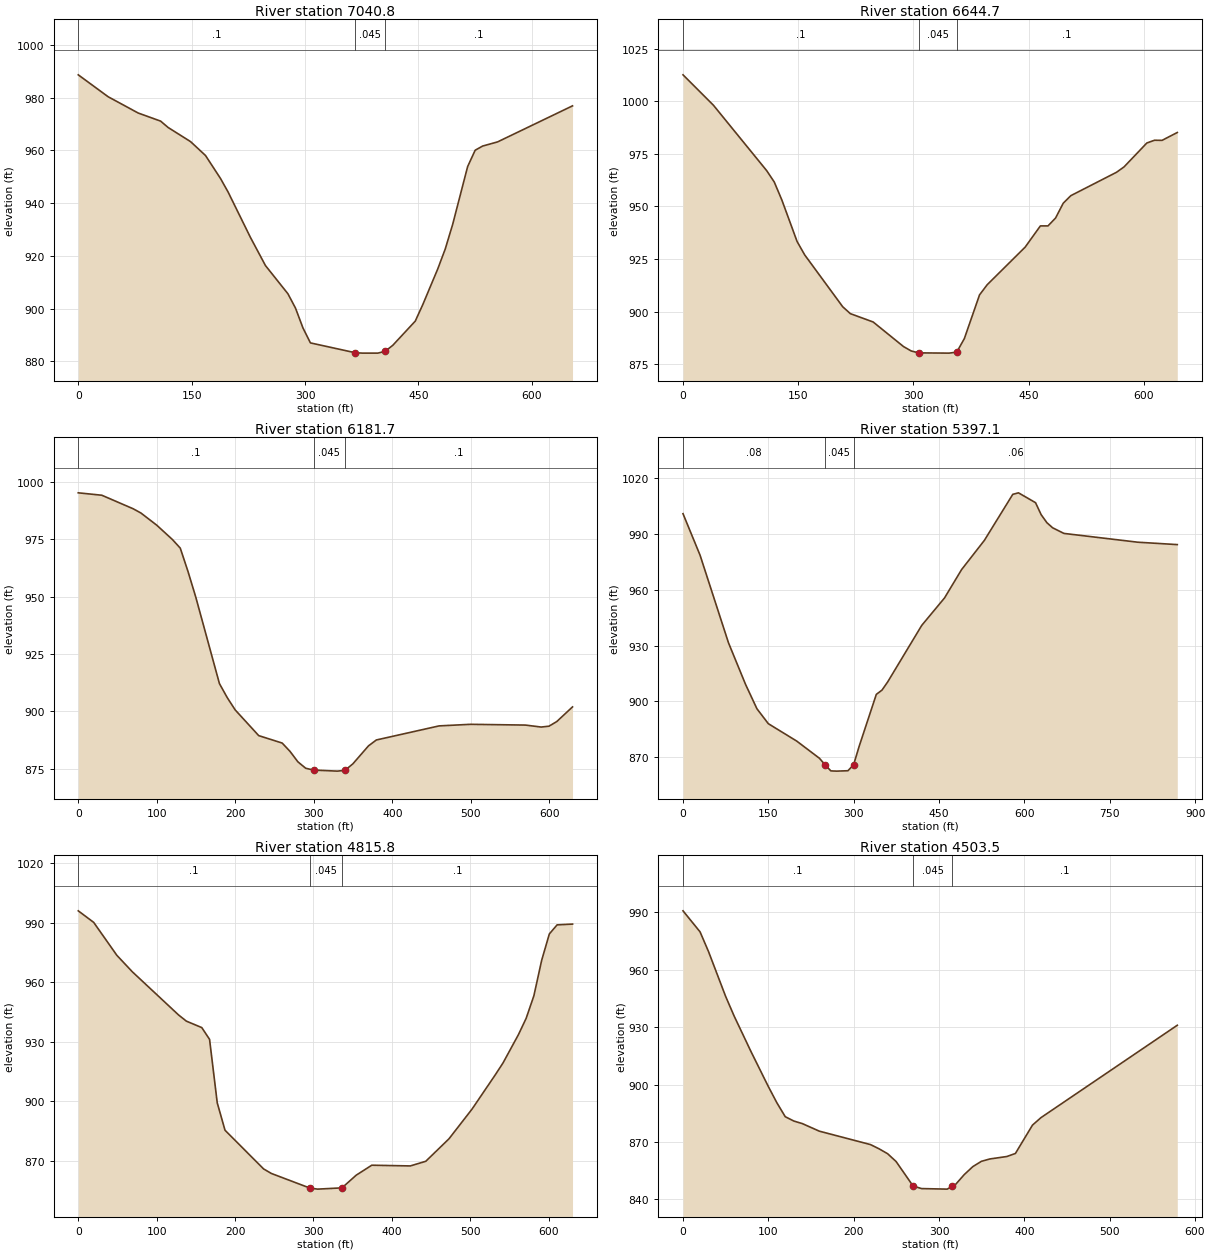
Type RM Length L Ch R = 1 ,7040.8  ,398.8,396.2,393.3
XS GIS Cut Line= 2
     1834171.654      390910.184     1834735.897      390579.566
#Sta/Elev= 30
       0  988.66    39.6  980.34    79.3  974.18     109  971.11   118.9   968.7
   148.6  963.34   168.4  958.07   188.3  949.33   198.2  944.27   227.9  926.99
   247.7  916.36   277.4  905.67   287.4  900.26   297.3  892.72   307.2  887.04
   366.6   883.3   376.5  883.16   396.4  883.16   406.2  883.86   416.2  886.13
   445.9  895.29   455.8   901.5   475.6  915.02   485.5  922.56   495.4  931.95
   515.2  953.87   525.2  960.08   535.1  961.66   554.9  963.24     654   976.9
#Mann= 3 , 0 , 0
       0      .1       0   366.6    .045       0   406.2      .1       0
Bank Sta=366.6,406.2
XS Rating Curve= 0 ,0
Exp/Cntr=0.3,0.1

Type RM Length L Ch R = 1 ,6644.7  ,462.2,463,463.8
XS GIS Cut Line= 2
     1834440.025      391251.649     1834947.707      390856.403
#Sta/Elev= 30
       0 1012.65    39.6  998.18   108.9  967.07   118.8  961.64   128.7  953.06
   148.5  933.34   158.4  926.97   207.9  902.29   217.8  899.02   247.5  895.05
     287  883.36     297  881.26   306.8  880.35   346.4  880.23   356.3   880.7
   366.2  887.13     386  907.95   395.9  912.75   445.4  930.68   465.2  940.77
   475.1  940.76     485  944.53   494.9  951.54   504.8  955.15   564.2  966.26
   574.1  968.84   603.8  980.22   613.7  981.52   623.6  981.47   643.4  985.21
#Mann= 3 , 0 , 0
       0      .1       0   306.8    .045       0   356.3      .1       0
Bank Sta=306.8,356.3
XS Rating Curve= 0 ,0
Exp/Cntr=0.3,0.1

Type RM Length L Ch R = 1 ,6181.7  ,776.3,784.5,792.8
XS GIS Cut Line= 2
     1834689.944      391610.545     1835208.024      391253.218
#Sta/Elev= 30
       0  995.36      30  994.31    69.9  988.41    79.9  986.53    99.9  981.26
   119.9  974.99   129.9  971.24   139.9  960.89   149.8  949.69   179.8  912.11
   189.8  905.98   199.8  900.67   229.8  889.44   259.7  886.19   269.7  882.55
   279.7     878   289.7  875.19   299.7  874.42   329.7  873.95   339.6  874.28
   349.6   877.1   369.6  884.97   379.6  887.54   459.5  893.68   499.5  894.37
   569.4  894.04   589.4  893.18   599.4  893.55   609.4  895.59   629.4  901.97
#Mann= 3 , 0 , 0
       0      .1       0   299.7    .045       0   339.6      .1       0
Bank Sta=299.7,339.6
XS Rating Curve= 0 ,0
Exp/Cntr=0.3,0.1

Type RM Length L Ch R = 1 ,5397.1  ,582.7,581.3,579.7
XS GIS Cut Line= 3
     1834640.148      392166.191     1835343.593      391973.497
     1835477.866      391936.716
#Sta/Elev= 30
       0 1000.87      30  978.55    79.9  931.54   109.9   909.2   129.9   896.1
   149.9  888.09   199.8  878.74   239.8  869.49   249.8  865.94   259.8  862.73
   269.8   862.6   289.8  862.81   299.7  865.97   309.7  876.08   339.7  903.82
   349.7  906.12   359.7  910.53   419.6  940.91   459.6  955.63   489.6  970.87
   529.5   986.5   579.5 1011.26   589.5 1012.08   619.5 1006.79   629.4 1000.33
   639.4  996.07   649.4  993.33   669.4  990.28     799  985.56   868.6  984.27
#Mann= 3 , 0 , 0
       0     .08       0   249.8    .045       0   299.7     .06       0
Bank Sta=249.8,299.7
XS Rating Curve= 0 ,0
Exp/Cntr=0.3,0.1

Type RM Length L Ch R = 1 ,4815.8  ,304.3,312.3,320.4
XS GIS Cut Line= 2
     1834909.904      392647.489     1835507.836      392447.486
#Sta/Elev= 30
       0  995.93    19.7   990.1    49.3  973.48      69   965.2   128.1   943.4
   137.9  940.34   157.6  937.07   167.5  931.15   177.3  899.16   187.2  885.36
   236.4  865.86   246.3  863.57   295.5   856.2   305.4  855.67   336.4856.3076
   354.6  862.71   374.4  867.72   423.6  867.36   443.3   869.7   472.9  881.03
   502.4  896.05     532   913.3   541.8  919.24   561.5  933.53   571.4   941.8
   581.2  953.12   591.1  970.93   600.9  984.26   610.8  988.85   630.5  989.24
#Mann= 3 , 0 , 0
       0      .1       0   295.5    .045       0   336.4      .1       0
Bank Sta=295.5,336.4
XS Rating Curve= 0 ,0
Exp/Cntr=0.3,0.1

Type RM Length L Ch R = 1 ,4503.5  ,1328.6,1343.1,1357.6
XS GIS Cut Line= 2
     1834895.465      392842.998      1835474.51      392858.388
#Sta/Elev= 30
       0  990.85      20  979.84      30  969.44    49.9  946.17    59.9  935.86
    79.9  917.06    99.9  899.08   109.9  890.59   119.8  883.24   129.8  880.98
   139.8  879.63   159.8  875.67   219.7  868.66   229.7  866.46   239.7  863.91
   249.7  859.81   269.6     847   279.6  845.66   309.6  845.38   315.3  846.83
   319.6  847.92   329.6  852.99   339.6  857.14   349.6   859.9   359.5  861.14
   379.5  862.43   389.5  864.02   409.5  878.83   419.5  882.76   579.2  931.04
#Mann= 3 , 0 , 0
       0      .1       0   269.6    .045       0   315.3      .1       0
Bank Sta=269.6,315.3
XS Rating Curve= 0 ,0
Exp/Cntr=0.3,0.1

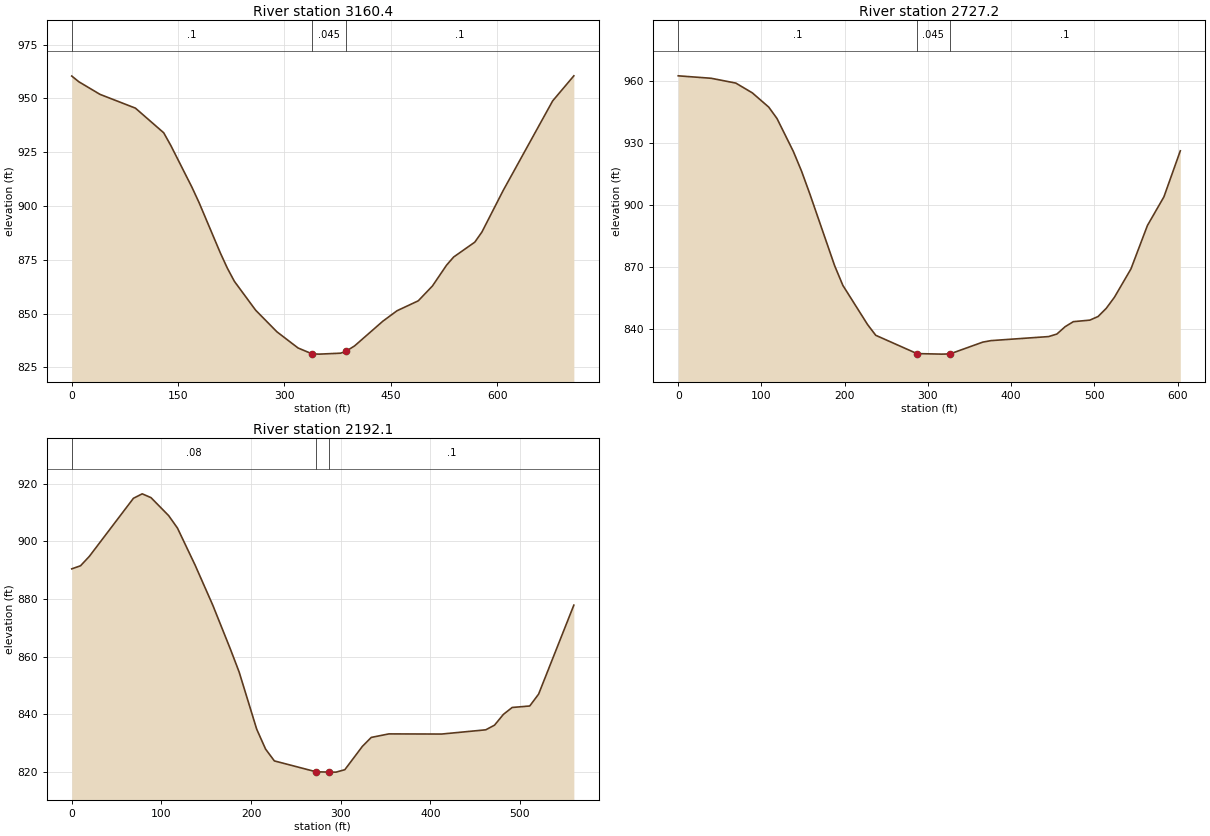
Type RM Length L Ch R = 1 ,3160.4  ,434.8,433.2,431.4
XS GIS Cut Line= 2
     1834434.708      393875.954     1834995.557      394308.507
#Sta/Elev= 30
       0  960.36      10   957.7    39.9  951.84    89.8  945.45   129.7     934
   139.7  928.12   169.6  908.67   179.6  901.56   209.5  878.26   219.5   871.1
   229.4     865   259.4  851.59   289.3  841.58   319.2  834.04   339.2  831.28
   349.2  831.18   379.1  831.61   386.4832.4138     399     835   438.9  846.49
   458.9  851.34   488.8  855.94   508.8  862.83   528.7  872.49   538.7  876.28
   568.6  883.21   578.6  887.89   608.5  907.13   678.4  948.81   708.3  960.46
#Mann= 3 , 0 , 0
       0      .1       0   339.2    .045       0   386.4      .1       0
Bank Sta=339.2,386.4
XS Rating Curve= 0 ,0
Exp/Cntr=0.3,0.1

Type RM Length L Ch R = 1 ,2727.2  ,543.2,535.1,527.1
XS GIS Cut Line= 2
     1834166.216       394238.12     1834671.382      394567.848
#Sta/Elev= 30
       0  962.67    39.6  961.48    69.2  959.14      89   954.4   108.8  947.46
   118.7  941.92   138.4  925.88   148.3  916.24   158.2  905.23   187.9  870.51
   197.8  860.93   227.5  841.91   237.3  836.71   286.8  827.83   316.5  827.57
   326.4  827.66   365.9   833.4   375.8  834.13     445  836.09   454.9  837.32
   464.8  840.88   474.7  843.33   494.5  844.07   504.4  845.83   514.2  849.79
   524.1  855.21   543.9  868.94   563.7  890.02   583.5  903.92   603.2  926.27
#Mann= 3 , 0 , 0
       0      .1       0   286.8    .045       0   326.4      .1       0
Bank Sta=286.8,326.4
XS Rating Curve= 0 ,0
Exp/Cntr=0.3,0.1

Type RM Length L Ch R = 1 ,2192.1  ,2195.4,2192.1,2187.3
XS GIS Cut Line= 2
     1834056.048      394866.079     1834602.449      394989.057
#Sta/Elev= 30
       0  890.46     9.8  891.54    19.6   894.8    68.8  914.98    78.6  916.53
    88.4   915.2   108.1  908.95   117.9  904.64   137.6  891.76   157.2  877.93
   176.9  862.62   186.7  854.64   206.3  834.76   216.2  827.85     226  823.74
   272.5  819.96   287.5  819.85   294.8  819.84   304.6  820.68   324.2  828.79
   334.1   831.9   353.7  833.12   412.7  833.07   461.8  834.54   471.6  836.15
   481.5   839.9   491.3   842.3   510.9  842.82   520.8  846.95   560.1  877.86
#Mann= 3 , 0 , 0
       0     .08       0   272.5    .045       0   287.5      .1       0
Bank Sta=272.5,287.5
XS Rating Curve= 0 ,0
Exp/Cntr=0.3,0.1

Chan Stop Cuts=-1
Use User Specified Reach Order=0
Composite Channel Slope=5